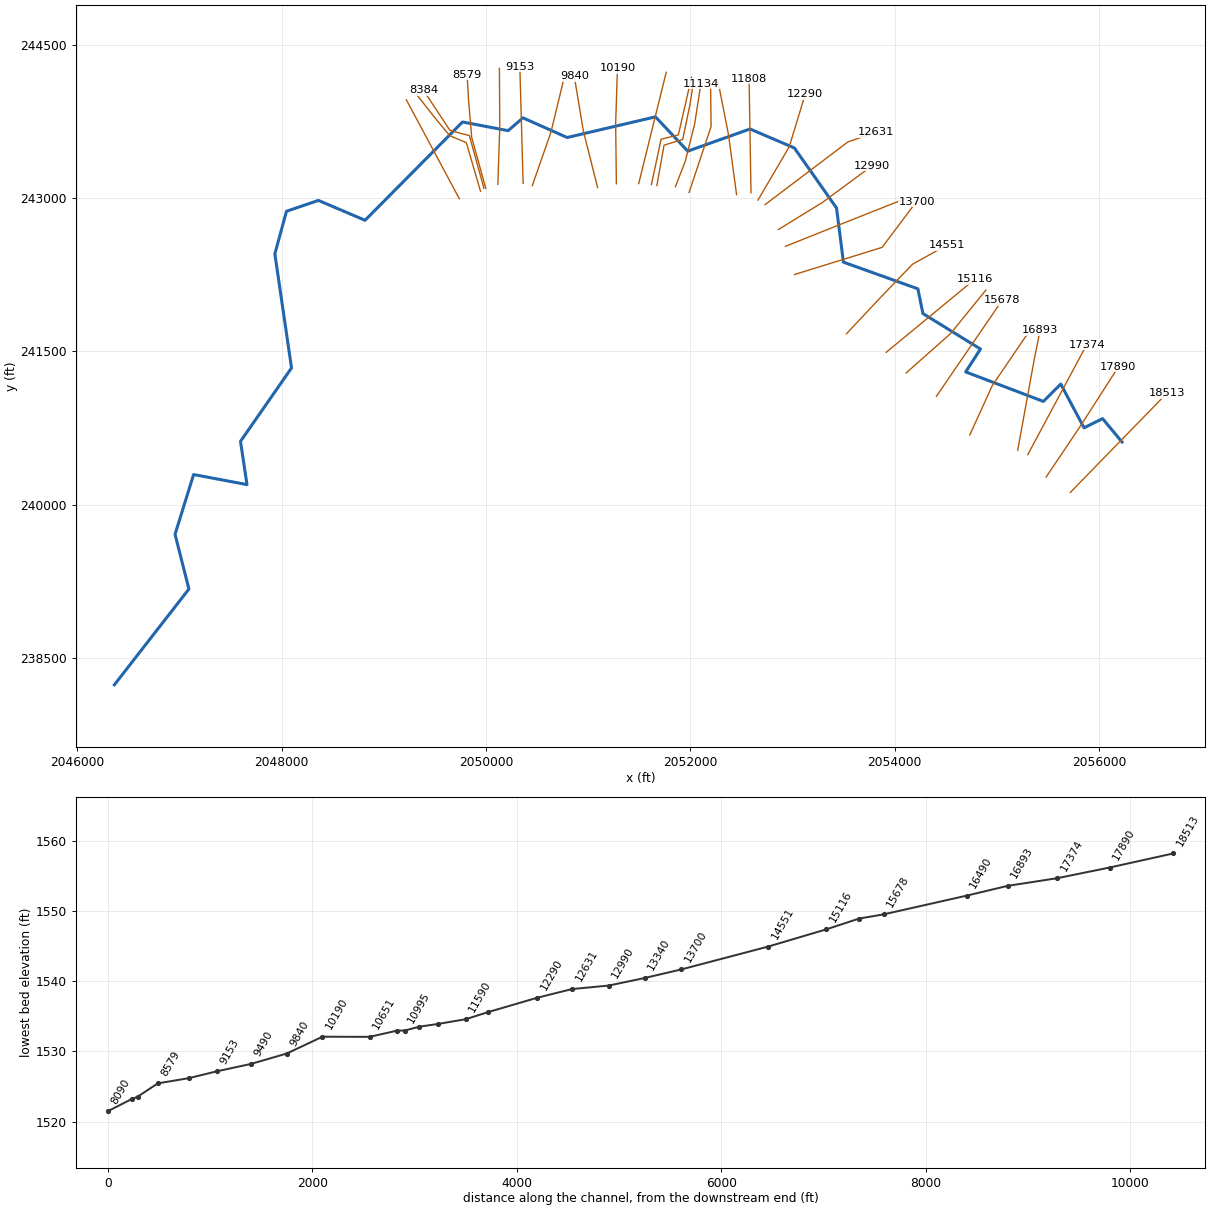
--- KELLYCK.prj (project) ---

Proj Title=KELLYCK
Current Plan=p01
Default Exp/Contr=0,0
English Units
Geom File=g01
Flow File=f01
Plan File=p01
BEGIN DESCRIPTION:
Stream Name: Kelly Creek
Flood Zone: Approximate
Summers County, West Virginia
HEC-RAS Version: 5.0.7
Hydrology Method:
Regression.
Model Notes:
END DESCRIPTION:
DSS Export Rating Curves= 0
DSS Export Rating Curve Sorted= 0
DSS Export Volume Flow Curves= 0
DXF OffsetX= 0
DXF OffsetY= 0
DXF ScaleX= 0
DXF ScaleY= 0

--- KELLYCK.p01 (plan) ---

Plan Title=Floodplain
Program Version=5.07
Short Identifier=Floodplain
Geom File=g01
Flow File=f01
Subcritical Flow
K Sum by GR= 0
Std Step Tol= 0.01
Critical Tol= 0.01
Num of Std Step Trials= 20
Max Error Tol= 0.3
Flow Tol Ratio= 0.001
Split Flow NTrial= 30
Split Flow Tol= 0.02
Split Flow Ratio= 0.02
Log Output Level= 0
Friction Slope Method= 1
Unsteady Friction Slope Method= 2
Unsteady Bridges Friction Slope Method= 1
Parabolic Critical Depth
Global Vel Dist= 0 , 0 , 0
Global Log Level= 0
CheckData=True
Encroach Param=-1 ,0,0, 0
Mapping Interval=1HOUR
Computation Time Step Use Courant=        0
Computation Time Step Use Time Series=    0
Computation Time Step Count To Double=0
Computation Time Step Max Doubling=0
Computation Time Step Max Halving=0
Computation Time Step Residence Courant=0
Run HTab= 0
Run UNet= 0
Run Sediment= 0
Run PostProcess= 0
Run WQNet= 0
Run RASMapper= 0
UNET Theta= 0
UNET Theta Warmup= 0
UNET ZTol= 0
UNET ZSATol= 0
UNET MxIter= 0
UNET Max Iter WO Improvement= 0
UNET MaxInSteps= 0
UNET DtIC= 0
UNET DtMin= 0
UNET MaxCRTS= 0
UNET WFStab= 0
UNET SFStab= 0
UNET WFX= 1
UNET SFX= 1
UNET 1D Methodology=Finite Difference
UNET DSS MLevel= 1
UNET Pardiso=0
UNET DZMax Abort= 0
UNET Use Existing IB Tables= 0
UNET Froude Reduction=False
UNET Froude Limit= 0
UNET Froude Power= 0
UNET D1 Cores= 0
UNET D2 Coriolis=0
UNET D2 Cores= 0
UNET D2 Theta= 1
UNET D2 Theta Warmup= 1
UNET D2 Z Tol= 0.01
UNET D2 Volume Tol= 0.01
UNET D2 Max Iterations= 20
UNET D2 Equation= 0
UNET D2 RampUpFraction=0.1
UNET D2 TimeSlices= 1
UNET D2 BCVolumeCheck=0
UNET D1D2 MaxIter= 0
UNET D1D2 ZTol=0.01
UNET D1D2 QTol=0.1
UNET D1D2 MinQTol=1
Write IC File= 0
Write IC File at Fixed DateTime=0
Write IC File at Sim End=0
Echo Input=False
Echo Parameters=False
Echo Output=False
Write Detailed= 0
HDF Write Warmup=0
HDF Write Time Slices=0
HDF Flush=0
HDF Face Node Velocities=0
HDF Compression= 1
HDF Chunk Size= 1
HDF Spatial Parts= 1
HDF Use Max Rows=0
HDF Fixed Rows= 1
Calibration Method= 0
Calibration Iterations= 20
Calibration Max Change=0.05
Calibration Tolerance=0.2
Calibration Maximum=1.5
Calibration Minimum=0.5
Calibration Optimization Method= 1
WQ AD Non Conservative
WQ ULTIMATE=-1
WQ Max Comp Step=1HOUR
WQ Output Interval=15MIN
WQ Output Selected Increments= 0
WQ Output face flow=0
WQ Output face velocity=0
WQ Output face area=0
WQ Output face dispersion=0
WQ Output cell volume=0
WQ Output cell surface area=0
WQ Output cell continuity=0
WQ Output cumulative cell continuity=0
WQ Output face conc=0
WQ Output face dconc_dx=0
WQ Output face courant=0
WQ Output face peclet=0
WQ Output face adv mass=0
WQ Output face disp mass=0
WQ Output cell mass=0
WQ Output cell source sink temp=0
WQ Output nsm pathways=0
WQ Output nsm derived pathways=0
WQ Output MaxMinRange=-1
WQ Daily Max Min Mean=-1
WQ Daily Range=0
WQ Daily Time=0
WQ Create Restart=0
WQ Fixed Restart=0
WQ System Summary=0
WQ Write To DSS=0
WQ Use Fixed Temperature=0
Sorting and Armoring Iterations= 10
XS Update Threshold= 0.02
Bed Roughness Predictor= 0
Hydraulics Update Threshold= 0.02
Energy Slope Method= 1
Volume Change Method= 1
Sediment Retention Method= 0
XS Weighting Method= 0
Number of US Weighted Cross Sections= 1
Number of DS Weighted Cross Sections= 1
Upstream XS Weight=0
Main XS Weight=1
Downstream XS Weight=0
Number of DS XS's Weighted with US Boundary= 1
Upstream Boundary Weight= 1
Weight of XSs Associated with US Boundary= 0
Number of US XS's Weighted with DS Boundary= 1
Downstream Boundary Weight= 0.5
Weight of XSs Associated with DS Boundary= 0.5
Percentile Method= 0
Sediment Output Level= 3
Mass or Volume Output= 0
Output Increment Type= 1
Profile and TS Output Increment= 1
XS Output Flag= 0
XS Output Increment= 10
Write Gradation File= 0
Read Gradation Hotstart= 0
Write HDF5 File= 1
Write Binary Output= 1
Write DSS Sediment File= 0
SV Curve= 0
Specific Gage Flag= 0

--- KELLYCK.f01 (steady flow) ---

Flow Title=Flows
Program Version=5.07
Number of Profiles= 6
Profile Names=01pct,10pct,04pct,02pct,0_2pct,01plus
River Rch & RM=KELLYCK,Main            ,18513
    1201     653     857    1023    1654    1776
River Rch & RM=KELLYCK,Main            ,16490
    1334     729     954    1138    1835    1974
River Rch & RM=KELLYCK,Main            ,10651
    1497     821    1073    1278    2054    2215
Boundary for River Rch & Prof#=KELLYCK,Main            , 1
Up Type= 0
Dn Type= 3
Dn Slope=0.00384
Boundary for River Rch & Prof#=KELLYCK,Main            , 2
Up Type= 0
Dn Type= 3
Dn Slope=0.00384
Boundary for River Rch & Prof#=KELLYCK,Main            , 3
Up Type= 0
Dn Type= 3
Dn Slope=0.00384
Boundary for River Rch & Prof#=KELLYCK,Main            , 4
Up Type= 0
Dn Type= 3
Dn Slope=0.00384
Boundary for River Rch & Prof#=KELLYCK,Main            , 5
Up Type= 0
Dn Type= 3
Dn Slope=0.00384
Boundary for River Rch & Prof#=KELLYCK,Main            , 6
Up Type= 0
Dn Type= 3
Dn Slope=0.00384
DSS Import GetInterval= 0
DSS Import GetPeak= 0
DSS Import FillOption= 0

--- KELLYCK.g01 (geometry) ---

Geom Title=Geometry
Program Version=5.07

River Reach=KELLYCK         ,Main
Reach XY= 30
2056224.97210667240613.554596973     2056034.434240842.721000002
2055853.01000002240752.4430000212055625.47200003241181.140000035
2055455.33300003241011.0010000172054694.91600003241300.063000029
2054839.88200002241524.0220000152054276.51399999241871.243999969
     2054227.035242113.431000028     2053498.736242374.715999991
2053431.02800001242905.0980000242053018.70100003243492.772000004
     2052584.673243678.5350000432051975.29900001243461.522000042
2051659.32600002243797.459000005     2050795.611243595.202000007
2050362.45099999243787.910000014     2050217.486243662.042000001
2049771.30500002243747.111999987     2048817.435      242784.526
2048360.95300001242979.3440000222048048.45299999242872.574000001
2047934.91100001242455.386000029     2048097.932241338.719000001
2047598.63500002240620.009000029     2047662.177240196.572000007
2047139.78100001240295.0090000462046958.01000001239709.593000009
     2047093.948239174.1760000222046364.04900001238235.783000031

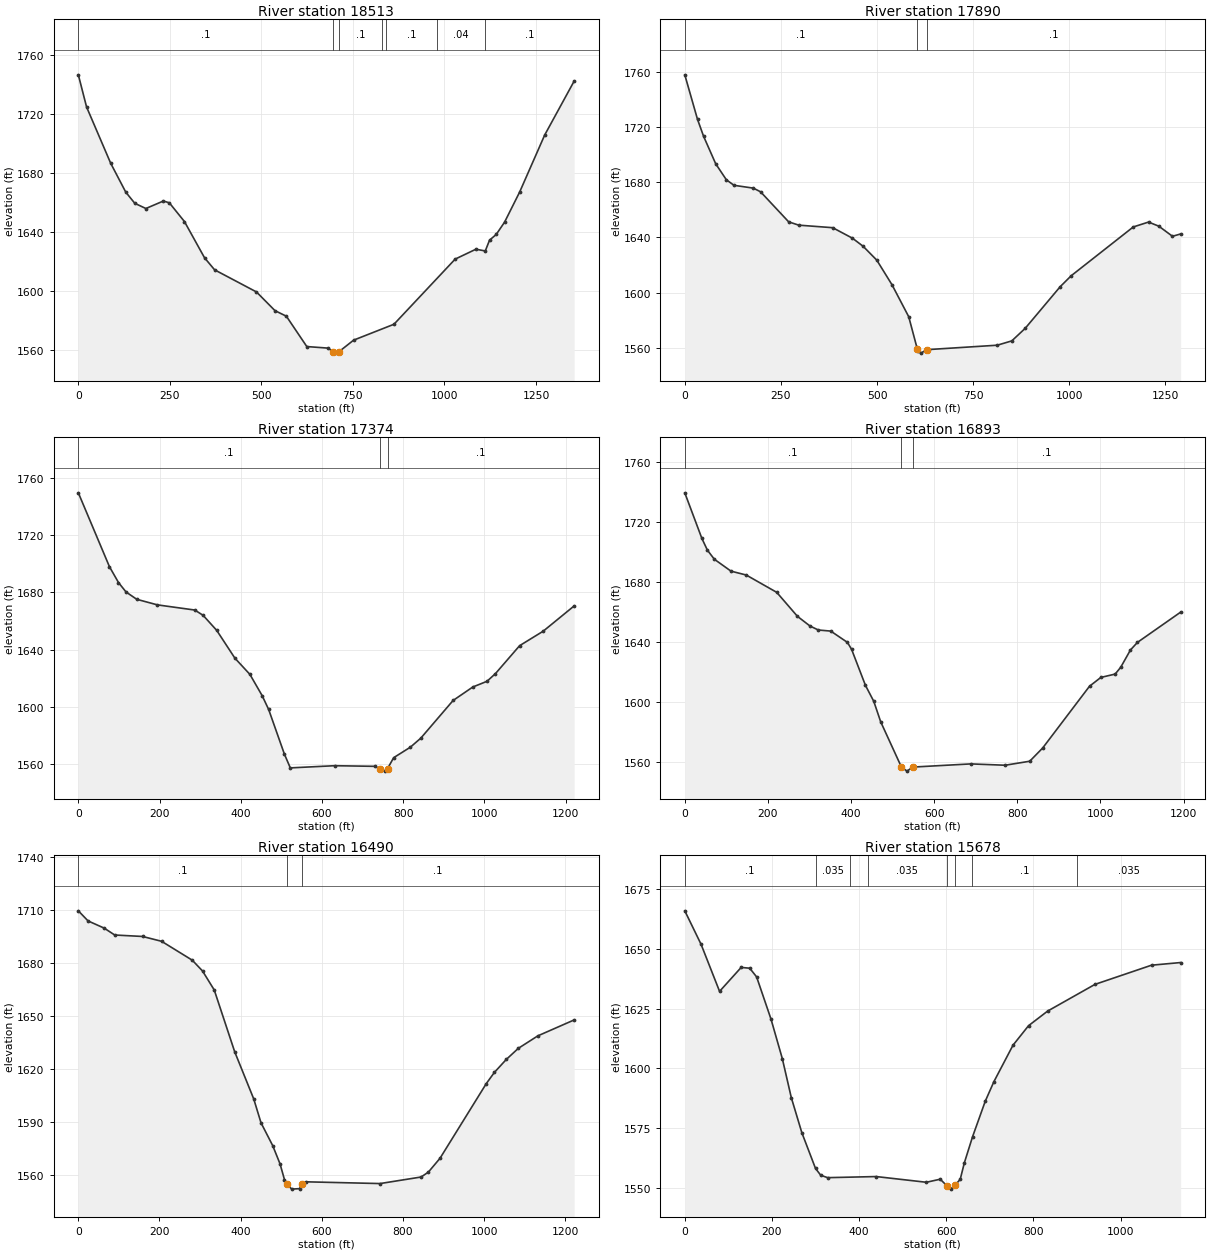
Type RM Length L Ch R = 1 ,18513   ,611.2,623.5,618.2
XS GIS Cut Line= 2
     2055719.287      240120.177     2056663.731      241090.664
#Sta/Elev= 30
       0 1746.27    22.5 1724.55    88.4  1686.5   129.5 1667.02   154.2 1659.45
   184.5 1655.94   232.2 1660.99   248.5  1659.8   289.8 1647.13   344.7 1622.63
   372.2  1614.5   486.6 1599.54     537 1586.93   568.2 1583.15     624 1562.65
   682.3 1561.59  696.131559.088   701.8 1558.21   711.51559.111   751.9 1566.99
     862 1577.71  1029.2 1621.74  1085.7 1628.41  1111.5 1627.26  1123.1 1634.54
  1141.3 1638.39  1164.2 1646.74  1205.4  1667.1  1273.8 1705.63  1354.2 1742.04
#Mann= 7 ,-1 , 0
       0      .1       0  696.13    .045       0   711.5      .1       0
     830    .035       0     840      .1       0     980     .04       0
    1110      .1       0
Bank Sta=696.13,711.5
XS Rating Curve= 0 ,0
Exp/Cntr=0.3,0.1

Type RM Length L Ch R = 1 ,17890   ,511,516.1,510.1
XS GIS Cut Line= 3
2055482.41940514 240270.81730099     2055826.792      240783.707
     2056189.278      241349.534
#Sta/Elev= 30
       0 1757.87    33.1 1725.57    48.9 1713.31    80.5 1693.35   108.2 1681.79
     128 1677.81   178.2 1675.77   197.1 1673.11   270.2 1651.33   296.4 1648.94
   384.8 1647.09   436.2 1639.47   463.9 1633.62   499.4 1623.59     539 1605.74
   582.5 1582.58  604.581559.445   606.1 1557.44     614  1556.2   629.7 1558.71
   812.8 1561.94   850.7 1565.08   885.5 1574.17   976.4  1604.3  1005.1 1612.26
  1166.6 1647.63  1206.3 1651.17  1233.1 1648.19  1268.6 1640.88  1289.8 1642.55
#Mann= 3 ,-1 , 0
       0      .1       0  604.58    .045       0   629.7      .1       0
Bank Sta=604.58,629.7
XS Rating Curve= 0 ,0
Exp/Cntr=0.3,0.1

Type RM Length L Ch R = 1 ,17374   ,478.3,481.2,481.9
XS GIS Cut Line= 2
      2055302.62      240489.969     2055879.009      241566.358
#Sta/Elev= 30
       0 1749.93    76.6 1698.12    98.9 1686.98   117.5 1680.36   143.9 1675.22
   194.8 1671.31   286.8 1667.69   307.3 1663.97   340.8 1653.42   385.5 1633.95
   422.5 1622.54   452.5 1607.72   468.7 1597.91   507.5 1566.57     522 1556.94
   631.1 1558.47   731.6 1558.03   742.8 1555.99   756.1 1554.67   761.4 1556.42
   776.5 1564.09   817.7 1571.48   843.3 1577.79   922.9 1604.25   971.5 1613.71
  1006.3 1617.68  1027.1 1623.06  1086.7 1642.69  1144.9 1652.88    1221 1670.59
#Mann= 3 ,-1 , 0
       0      .1       0   742.8    .045       0   761.4      .1       0
Bank Sta=742.8,761.4
XS Rating Curve= 0 ,0
Exp/Cntr=0.3,0.1

Type RM Length L Ch R = 1 ,16893   ,404.4,402.7,386.8
XS GIS Cut Line= 3
     2055203.951      240533.4742055371.14693439  241450.6957247
     2055423.055      241705.964
#Sta/Elev= 30
       0  1739.2    41.1 1708.77    54.4 1700.95    71.1  1694.9   111.1 1686.97
   147.8 1684.38   221.2 1672.82     271 1656.82   301.2 1650.37   321.2 1647.71
   351.2 1646.98   391.3 1639.44   401.3 1634.78   434.6 1610.79   454.6 1600.15
   471.3 1586.47   521.3  1556.2   534.7 1553.59     548 1556.28   688.1 1558.41
   770.6 1557.52   829.8 1560.19   860.9    1569   973.7 1610.23  1000.9 1616.08
  1035.3 1618.32  1048.7 1622.86  1072.1 1634.39  1088.9 1639.45  1192.8 1659.62
#Mann= 3 ,-1 , 0
       0      .1       0   521.3    .045       0     548      .1       0
Bank Sta=521.3,548
XS Rating Curve= 0 ,0
Exp/Cntr=0.3,0.1

Type RM Length L Ch R = 1 ,16490   ,815.8,812,633.6
XS GIS Cut Line= 3
     2054734.991      240682.581     2054956.119      241167.752
     2055343.536      241737.048
#Sta/Elev= 30
       0 1709.72      24    1704    63.6 1699.94    89.7 1696.03   158.2 1695.21
   205.1 1692.48   280.8 1681.77     306 1675.68   334.9 1664.92   385.3 1629.94
   432.2 1603.25   450.2  1589.7   479.1 1576.76   497.1 1566.44   507.9 1557.63
   514.4  1554.9     526 1552.19   545.1 1552.47   550.7 1554.82     561 1556.33
   743.5 1555.34   844.6 1559.05   862.6 1561.83   891.3 1569.67  1005.4 1611.97
  1025.3 1618.28  1054.5 1625.59  1084.3  1631.9  1132.4 1638.96  1221.8 1647.97
#Mann= 3 ,-1 , 0
       0      .1       0   514.4    .045       0   550.7      .1       0
Bank Sta=514.4,550.7
XS Rating Curve= 0 ,0
Exp/Cntr=0.3,0.1

Type RM Length L Ch R = 1 ,15678   ,242.2,238,235.8
XS GIS Cut Line= 2
     2054408.523       241061.15     2055050.884      242000.386
#Sta/Elev= 30
       0 1665.97    37.3 1651.98    79.8 1632.27   129.4 1642.29     149 1641.96
   164.8 1638.33   197.8 1620.68   223.8 1604.13   244.4 1587.83   268.6 1573.14
     300 1558.17     312 1555.32   327.9 1554.32   439.2 1554.78   554.4 1552.39
   586.2 1553.67   601.4 1550.94   610.1 1549.52   620.3 1551.18   632.1 1553.63
   641.6 1560.55   660.4 1571.44   689.6 1586.33   709.4  1594.5   753.2 1609.74
   788.9 1617.91   832.7 1624.02   941.3 1635.19  1071.1 1643.22  1137.9 1644.33
#Mann= 8 ,-1 , 0
       0      .1       0     300    .035       0     380      .1       0
     420    .035       0   601.4    .045       0   620.3    .035       0
     660      .1       0     900    .035       0
Bank Sta=601.4,620.3
XS Rating Curve= 0 ,0
Exp/Cntr=0.3,0.1

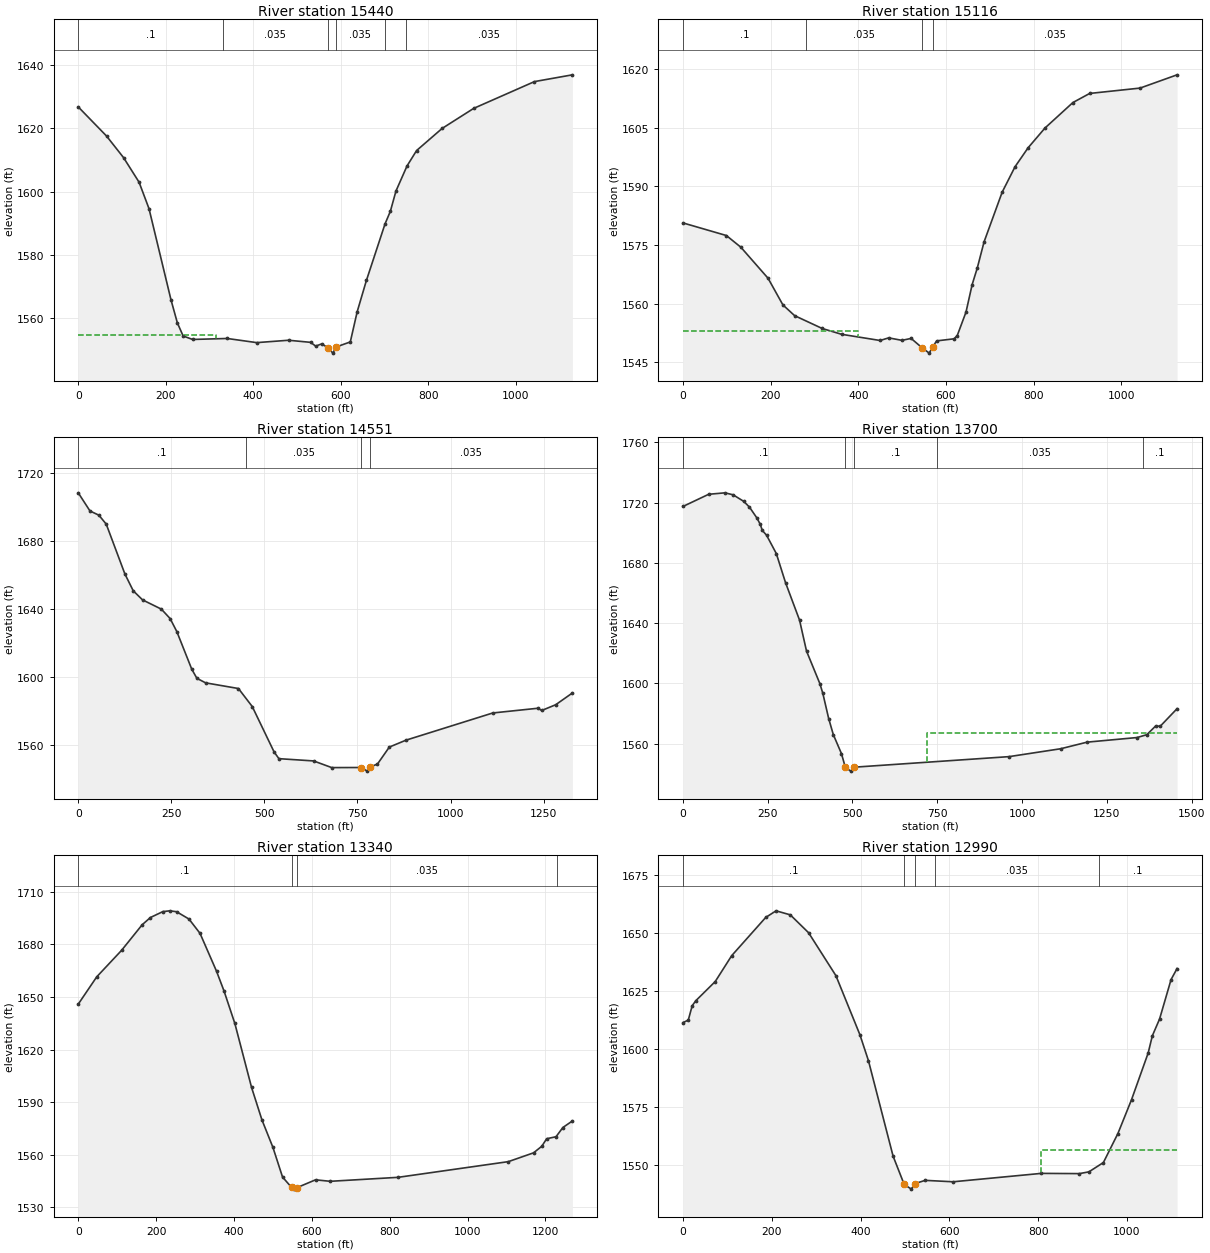
Type RM Length L Ch R = 1 ,15440   ,318.6,324.1,309.8
XS GIS Cut Line= 3
     2054111.831       241289.61     2054546.381      241674.293
     2054892.487      242101.268
#Sta/Elev= 30
       0 1626.75    64.6 1617.56   103.7  1610.7   139.1 1602.95   161.8 1594.59
   212.1 1565.76   226.7 1558.46   239.9 1554.34   261.6 1553.25   340.6 1553.56
   408.1 1552.25   480.9    1553   531.3 1552.34   542.9 1551.15   556.9 1551.86
   570.8 1550.61   582.4 1548.93   589.4 1550.86   622.1 1552.47   637.8    1562
   658.9 1571.89   701.4 1589.73   713.8  1593.8   726.5 1600.16   751.8 1608.09
   773.7 1612.96     832 1619.94   904.3 1626.29  1043.2 1634.75    1130 1636.89
#Mann= 6 ,-1 , 0
       0      .1       0     330    .035       0   570.8    .045       0
   589.4    .035       0  700.36      .1       0  750.36    .035       0
#XS Ineff= 2 , 0
          314.29 1554.57
Permanent Ineff=
       F       F
Bank Sta=570.8,589.4
XS Rating Curve= 0 ,0
Exp/Cntr=0.3,0.1

Type RM Length L Ch R = 1 ,15116   ,556.1,564.9,563.2
XS GIS Cut Line= 2
     2053917.203      241491.705     2054786.331      242208.997
#Sta/Elev= 30
       0 1580.67    99.2 1577.44   132.2 1574.45   194.2 1566.52   228.1  1559.7
   254.8 1556.96   317.7 1553.68     362 1552.19   449.7 1550.61   469.2 1551.28
   499.5 1550.65   520.5 1551.14   546.1 1548.68   561.8 1547.38   569.4 1548.97
   578.8 1550.51   618.3 1551.04   625.6 1551.86   645.6 1557.87   659.6 1564.89
   671.4 1569.17   686.8 1575.82   728.1 1588.53   757.5 1595.04   787.2 1599.87
   825.7 1604.92   889.3 1611.43   927.6 1613.76  1042.5 1615.13  1126.9 1618.52
#Mann= 4 ,-1 , 0
       0      .1       0     280    .035       0   546.1    .045       0
   569.4    .035       0
#XS Ineff= 2 , 0
          400.33 1553.03
Permanent Ineff=
       F       F
Bank Sta=546.1,569.4
XS Rating Curve= 0 ,0
Exp/Cntr=0.3,0.1

Type RM Length L Ch R = 1 ,14551   ,849.5,850.6,826.3
XS GIS Cut Line= 4
2053528.43449949241673.5478793012053855.66317854242022.304760918
2054174.28057656 242353.839080482054514.42617715242543.287263087
#Sta/Elev= 30
       0 1708.16    31.5 1697.52    55.4 1695.05    75.2  1689.8   125.2 1660.63
   147.7  1650.7   172.7 1645.38   223.3 1639.94   246.7 1634.44   264.7 1626.83
   304.8 1604.78   318.7 1599.36   342.1 1596.72   430.3 1593.39   467.4 1582.82
   526.1 1556.17     539 1552.25   632.2 1550.92   680.9 1547.01   759.8 1547.06
   776.4 1544.94     783 1547.34   803.7 1549.08   835.6 1559.05   880.5 1563.11
  1113.5 1579.05  1235.2 1581.83  1244.8  1580.5  1282.5 1583.88  1327.4 1590.78
#Mann= 4 ,-1 , 0
       0      .1       0     450    .035       0   759.8    .045       0
     783    .035       0
Bank Sta=759.8,783
XS Rating Curve= 0 ,0
Exp/Cntr(USF)=0,0
Exp/Cntr=0.3,0.1

Type RM Length L Ch R = 1 ,13700   ,356.3,360.4,358
XS GIS Cut Line= 3
      2053021.37      242253.858     2053877.273      242519.483
2054213.87285593242968.027496441
#Sta/Elev= 30
       0 1717.44      76 1725.55   124.1 1726.52   148.1  1725.2     179  1720.9
   196.2 1717.06   217.8 1709.95   228.3 1705.53     234 1701.57   246.6  1698.4
   275.4  1686.2   302.7 1666.81   343.9    1642   364.5 1621.42   403.9 1599.78
   412.6 1593.33   429.8 1576.63   443.5 1565.93   467.6 1553.26     479 1544.14
   495.1 1541.68   505.4  1544.3   961.8 1551.31  1113.5 1556.53    1192 1560.94
  1339.1 1563.99  1367.7 1565.87  1393.5 1571.57  1407.6 1571.54    1457 1583.16
#Mann= 5 ,-1 , 0
       0      .1       0     479    .045       0   505.4      .1       0
     750    .035       0 1356.17      .1       0
#XS Ineff= 2 , 0
                          719.77         1566.78
Permanent Ineff=
       F       F
Bank Sta=479,505.4
XS Rating Curve= 0 ,0
Exp/Cntr=0.3,0.1

Type RM Length L Ch R = 1 ,13340   ,341.3,350,348.7
XS GIS Cut Line= 3
     2052931.609      242529.615     2053450.399      242737.243
2054110.80785593242999.146607707
#Sta/Elev= 30
       0 1645.91    47.6  1661.5   111.2 1676.55   164.2 1691.17   185.4 1695.29
   217.2 1698.65   234.9  1699.1   252.6 1698.59   284.4 1694.41   312.7 1686.28
   355.1  1664.7   374.5 1653.34   402.2 1634.89   445.1 1598.44   471.7 1579.97
     500 1564.24   524.7 1547.33  548.041541.389     553 1540.45   562.11541.332
   609.4 1545.75   647.2 1544.91   821.2 1547.17  1104.6 1556.12  1169.4 1561.14
  1190.5 1564.89  1203.1 1569.18  1227.1 1570.32  1244.7 1575.58  1269.2 1579.32
#Mann= 4 ,-1 , 0
       0      .1       0  548.04    .045       0   562.1    .035       0
  1228.8      .1       0
Bank Sta=548.04,562.1
XS Rating Curve= 0 ,0
Exp/Cntr=0.3,0.1

Type RM Length L Ch R = 1 ,12990   ,351.9,358.9,358.1
XS GIS Cut Line= 3
2052862.83224822242694.480470752      2053294.81      242960.496
     2053781.781      243320.273
#Sta/Elev= 30
       0 1611.29    12.1 1612.36      21  1618.6    29.1 1620.75    72.9 1629.04
   109.9  1640.2   186.6 1656.72   209.8 1659.56   241.8 1657.83     283 1650.11
   344.6 1631.56   398.6 1606.06   417.8 1594.89   473.3 1553.65   498.3 1541.41
   514.5 1539.38   522.2 1541.74   545.6 1543.17   608.4 1542.55   807.2 1546.18
   892.8 1546.08   914.3 1546.84   946.9 1550.86   979.6  1563.4  1010.3 1578.02
  1047.7 1598.14  1057.1 1605.58  1073.4 1612.83  1099.3 1629.88  1112.8 1634.64
#Mann= 5 ,-1 , 0
       0      .1       0   498.3    .045       0   522.2      .1       0
  567.32    .035       0  937.32      .1       0
#XS Ineff= 2 , 0
                          806.59         1556.25
Permanent Ineff=
       F       F
Bank Sta=498.3,522.2
XS Rating Curve= 0 ,0
Exp/Cntr=0.3,0.1

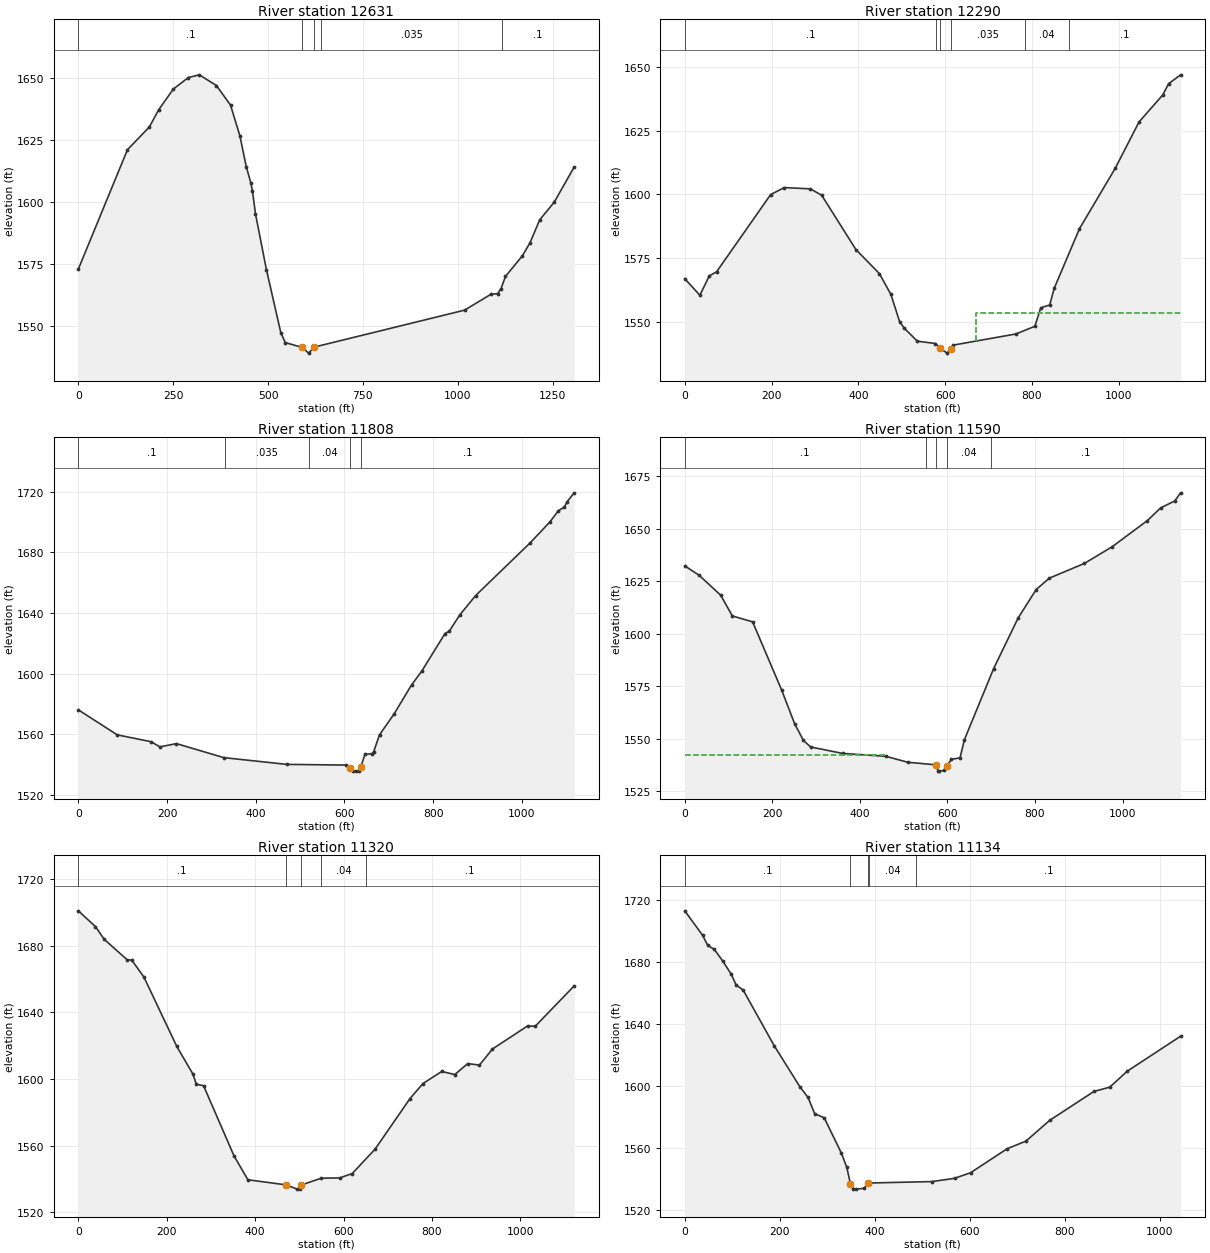
Type RM Length L Ch R = 1 ,12631   ,331.4,341.1,352.2
XS GIS Cut Line= 3
      2052731.44      242937.8862053542.41316976243551.912235376
2053816.16944367243646.908164034
#Sta/Elev= 30
       0 1572.76   129.6 1620.94   187.2 1630.06   211.9 1637.04   250.5 1645.39
   290.1 1650.02   318.9 1651.11   364.1 1646.79   401.2 1638.88   425.9 1626.49
   442.7 1614.04   454.7 1607.56   458.9 1604.41     467 1595.04   495.8 1572.56
   533.8 1547.12   545.5 1543.13   590.5 1541.17   606.9 1538.88   622.1 1541.33
  1018.3 1556.22  1087.7 1562.63  1105.1 1562.83  1114.2 1564.88  1125.9  1569.8
  1170.4  1578.1  1190.4 1583.31  1216.2 1592.63  1254.4 1599.74    1307 1613.91
#Mann= 5 ,-1 , 0
       0      .1       0   590.5    .045       0   622.1      .1       0
     640    .035       0  1117.2      .1       0
#XS Ineff= 2 , 0
                          767.79         1546.62
Permanent Ineff=
       F       F
Bank Sta=590.5,622.1
XS Rating Curve= 0 ,0
Exp/Cntr=0.3,0.1

Type RM Length L Ch R = 1 ,12290   ,458.7,481.5,481.8
XS GIS Cut Line= 3
     2052662.291      242982.204     2052968.024      243503.949
     2053124.973      244018.636
#Sta/Elev= 30
       0 1566.88    34.8 1560.39    56.4 1568.01    73.2 1569.59   197.8 1599.94
     229 1602.71   289.2 1602.21   315.4 1599.73   394.4 1578.35   448.5  1568.9
   475.1  1560.7   495.1 1550.02   505.6 1547.49   535.9 1542.34   577.8 1541.42
   589.2 1539.47   604.4 1537.64   612.4 1539.22   618.2 1540.78   763.2 1545.17
   806.8 1548.19   820.5 1555.46   841.1 1556.57   851.4  1563.1   909.7 1586.56
   991.9 1610.24  1046.9  1628.5  1101.8 1639.16  1115.1 1643.55  1142.8 1647.03
#Mann= 6 ,-1 , 0
       0      .1       0     580    .035       0   589.2    .045       0
   612.4    .035       0  784.72     .04       0  884.72      .1       0
#XS Ineff= 2 , 0
                          670.49         1553.38
Permanent Ineff=
       F       F
Bank Sta=589.2,612.4
XS Rating Curve= 0 ,0
Exp/Cntr=0.3,0.1

Type RM Length L Ch R = 1 ,11808   ,216.3,218.5,222.1
XS GIS Cut Line= 2
     2052594.287      243054.205      2052575.19      244172.261
#Sta/Elev= 30
       0 1576.04    87.8 1559.52   164.1 1555.01   183.8  1551.6   221.3 1553.74
   328.1  1544.5   470.1 1540.04   603.8 1539.58   613.6 1537.96   620.2 1535.72
   625.3 1535.59   633.3 1535.89   636.6 1538.06   646.4 1546.57   662.8 1547.17
   666.1 1548.43   679.2 1559.53   712.1 1573.34   751.4 1592.45   774.4 1601.54
   826.9  1626.4   836.7 1627.98   859.7 1638.46   895.8 1651.42  1018.6 1686.13
  1063.2 1699.95  1082.8 1707.52    1096 1709.81  1102.5 1713.44  1118.2 1719.26
#Mann= 5 ,-1 , 0
       0      .1       0     330    .035       0     520     .04       0
   613.6    .045       0   636.6      .1       0
Bank Sta=613.6,636.6
XS Rating Curve= 0 ,0
Exp/Cntr=0.3,0.1

Type RM Length L Ch R = 1 ,11590   ,286.1,269.6,257.5
XS GIS Cut Line= 3
     2052452.859      243035.175     2052374.708      243618.589
     2052270.008      244152.259
#Sta/Elev= 30
       0 1632.35    32.5 1627.94    82.1 1618.36   108.6 1608.51   154.9 1605.71
   221.1 1573.28   250.9 1557.13   270.8 1549.27   287.4 1546.09   360.2 1543.03
   459.5 1541.63   509.1 1538.81   573.3 1537.59   578.6 1534.72   581.7 1534.58
   591.9 1534.88   598.6 1536.88   608.6 1540.12   628.7 1540.95   638.7 1549.59
   705.3 1583.38   761.2 1607.48   802.5 1621.08   832.6 1626.52   912.9 1633.55
   976.3  1641.5  1056.6 1653.95  1086.7 1659.97    1119 1663.29  1132.5 1667.17
#Mann= 5 ,-1 , 0
       0      .1       0     550     .04       0   573.3    .045       0
   598.6     .04       0  698.63      .1       0
#XS Ineff= 2 , 0
          457.86 1542.38
Permanent Ineff=
       F       F
Bank Sta=573.3,598.6
XS Rating Curve= 0 ,0
Exp/Cntr=0.3,0.1

Type RM Length L Ch R = 1 ,11320   ,177.4,186.4,182.2
XS GIS Cut Line= 3
     2051988.384      243057.677     2052203.662      243703.511
     2052198.454      244144.483
#Sta/Elev= 30
       0 1701.04    38.7 1691.58    58.6 1683.92   110.5 1671.64   120.9 1671.44
   148.5  1661.2   222.8 1619.59   259.2 1603.04   266.9 1596.98   283.4 1595.97
   352.5 1553.73   383.7 1539.52   469.2  1536.5   495.2 1533.91   501.3 1534.24
   504.7 1536.43   549.7 1540.47   591.1 1540.63   619.7 1543.27   671.6 1557.99
     750 1588.16   779.5 1597.28   822.2 1604.59   851.7 1602.71     881  1609.3
   907.5  1608.4     937 1618.07  1017.2 1632.04  1033.4 1631.64  1121.8 1655.95
#Mann= 5 ,-1 , 0
       0      .1       0   469.2    .045       0   504.7      .1       0
     550     .04       0     650      .1       0
Bank Sta=469.2,504.7
XS Rating Curve= 0 ,0
Exp/Cntr=0.3,0.1

Type RM Length L Ch R = 1 ,11134   ,170.3,139,110.1
XS GIS Cut Line= 4
2051854.62806836243114.220788283 2051951.2406997243363.379679649
2052042.76845572243726.9482660282052103.78695972244123.568542079
#Sta/Elev= 30
       0 1712.97    37.7 1697.07    48.2 1690.64      62 1688.14    79.9 1680.57
    97.5 1672.21   108.1 1665.13   122.9 1661.86   188.2 1625.94     242 1599.63
   259.4  1592.6   273.2 1582.23   293.5 1579.46   329.6 1556.69   340.9 1547.52
   348.5  1537.1   353.9 1533.88   361.2 1533.51   378.1 1534.04   384.9 1537.43
   520.2 1538.38   567.6 1540.47   601.4 1544.07   678.5 1559.59   717.9 1564.47
   768.1 1577.92   861.1 1596.52   894.3 1599.26   930.7 1609.48  1043.4 1632.13
#Mann= 5 ,-1 , 0
       0      .1       0   348.5    .045       0   384.9      .1       0
  387.23     .04       0  487.23      .1       0
Bank Sta=348.5,384.9
XS Rating Curve= 0 ,0
Exp/Cntr(USF)=0,0
Exp/Cntr=0.5,0.3

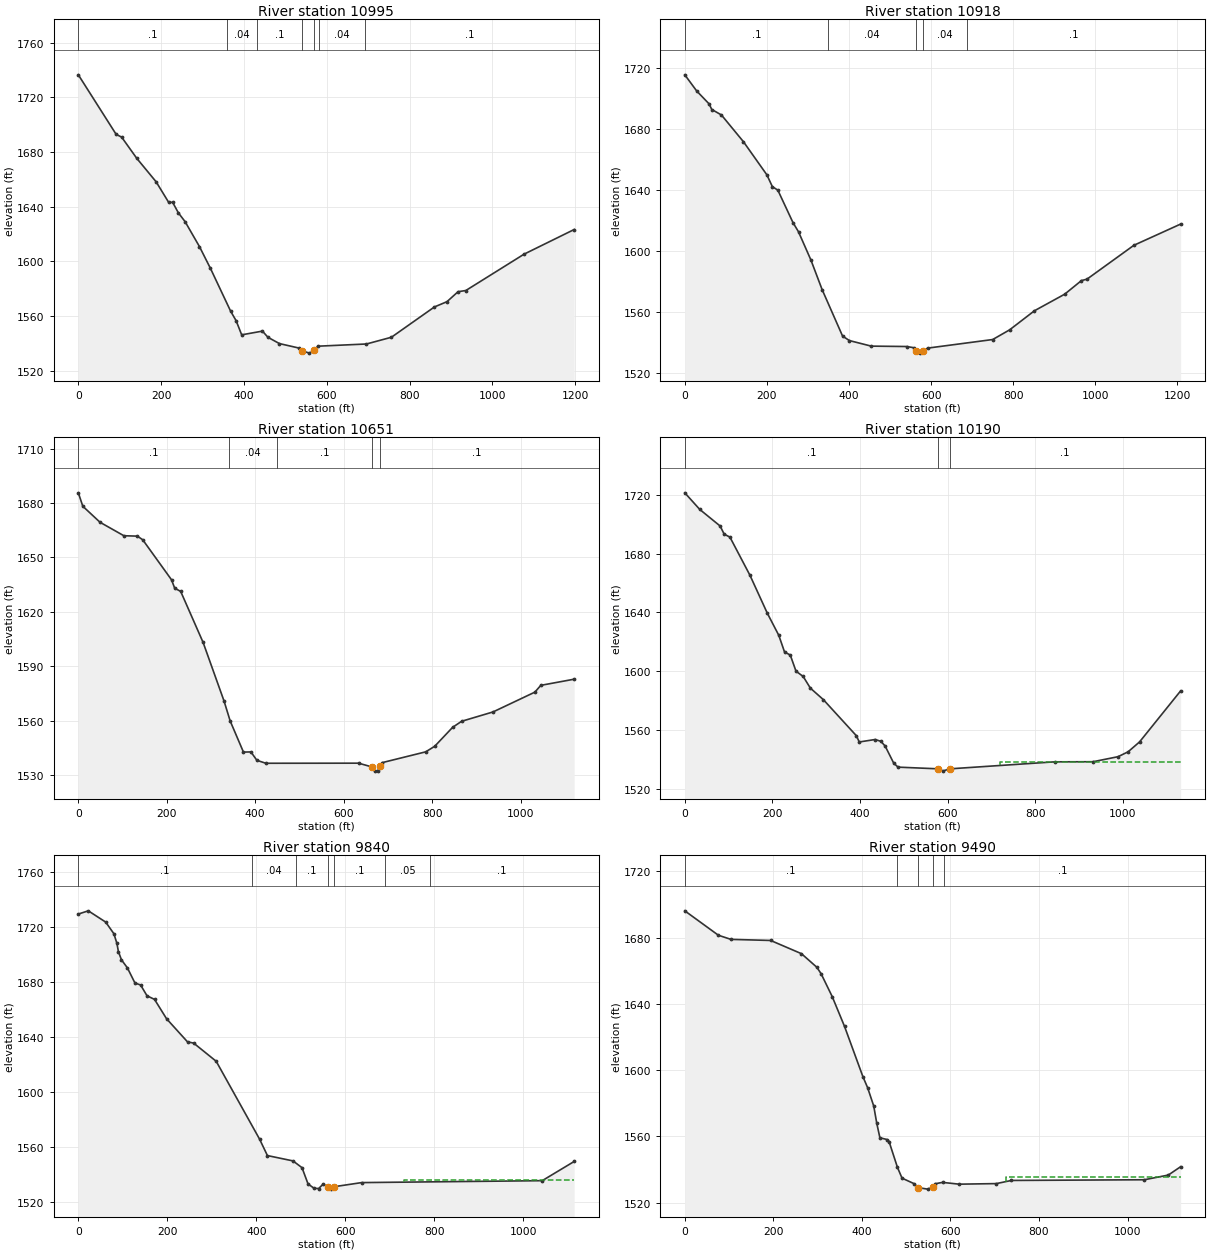
Type RM Length L Ch R = 1 ,10995   ,73.4,76.8,72.5
XS GIS Cut Line= 5
2051673.30705629243125.1342104852051743.47812645243520.353680803
2051925.81893678243575.9313438712051998.12812938243922.149516481
     2052035.611      244171.131
#Sta/Elev= 30
       0 1736.39    91.3 1692.89   104.6 1690.85   141.2 1675.33   187.9 1658.19
   217.9 1643.32   227.9 1643.13   241.6  1635.5   257.9 1629.05   292.6 1610.81
   319.2 1594.84   367.8 1563.65   381.1 1556.66   394.5 1546.34   444.7 1549.07
     458 1544.52   485.8 1539.93   533.9 1536.61 540.7161534.735   557.8 1532.97
 569.3141534.897   578.4 1538.04   695.9 1539.65   756.2 1544.58   860.1 1566.74
   890.3 1570.57   917.1 1577.87   935.9 1578.74  1076.6 1605.32  1197.5 1623.32
#Mann= 7 ,-1 , 0
       0      .1       0     360     .04       0   431.4      .1       0
 540.716    .045       0 569.314      .1       0   581.4     .04       0
  692.02      .1       0
#XS Ineff= 2 ,-1
       0     531 1536.79  577.261197.499 1537.21
Permanent Ineff=
       F       F
Bank Sta=540.716,569.314
XS Rating Curve= 0 ,0
Exp/Cntr=0.5,0.3

Type RM Length L Ch R = 1 ,10918   ,243.5,267.2,291.9
XS GIS Cut Line= 4
2051619.90287741243134.2492104852051714.10651859243578.489386747
2051883.32260379243620.571415146     2052012.173      244185.454
#Sta/Elev= 30
       0  1715.3    28.9 1704.75      59  1696.3    65.8 1692.58    89.2 1689.01
   142.9 1671.46   199.9 1649.79   213.3 1642.04   226.7 1639.72   263.6 1618.45
     277 1612.45   307.2 1593.98   334.5  1574.6   384.4  1544.1   401.1 1541.17
   454.1 1537.54   540.6 1537.28   557.5 1536.52  562.99 1534.34   572.6 1532.95
 580.7551534.198   591.3 1536.22   750.1 1541.86   791.3  1548.2   851.8 1560.71
   925.4 1571.56   966.3 1580.49   979.7  1581.4  1094.1 1603.62  1207.9 1617.51
#Mann= 5 ,-1 , 0
       0      .1       0     350     .04       0  562.99    .045       0
 580.755     .04       0  688.49      .1       0
#XS Ineff= 2 ,-1
       0   555.7 1535.62  590.56 1207.88 1535.54
Permanent Ineff=
       F       F
Bank Sta=562.99,580.755
XS Rating Curve= 0 ,0
Exp/Cntr=0.5,0.3

Type RM Length L Ch R = 1 ,10651   ,455,461.1,462.6
XS GIS Cut Line= 2
     2051495.329      243144.483     2051764.426      244233.025
#Sta/Elev= 30
       0 1685.66    10.1 1678.26      49 1669.42     103 1661.98   133.5 1661.76
   145.6 1659.76   210.7 1637.68   217.9 1633.05   231.5 1631.24   282.2 1603.08
   329.5 1570.77   343.4 1559.74   373.4 1542.58   390.3 1542.67   403.8 1538.03
   424.1 1536.41   633.6 1536.46   663.2 1534.44   670.8 1532.07   677.6 1532.41
   682.2 1534.71   687.7 1536.79   785.7 1542.72     806  1545.8   846.5 1556.25
   866.8 1559.58   937.8 1564.73  1032.4 1575.66  1045.9 1579.41  1121.3 1582.81
#Mann= 5 ,-1 , 0
       0      .1       0     340     .04       0     450      .1       0
   663.2    .045       0   682.2      .1       0
Bank Sta=663.2,682.2
XS Rating Curve= 0 ,0
Exp/Cntr=0.3,0.1

Type RM Length L Ch R = 1 ,10190   ,342,350,353.4
XS GIS Cut Line= 3
     2051276.749      243141.512     2051269.763      243733.796
     2051287.419      244273.158
#Sta/Elev= 30
       0  1721.3    34.1 1710.03    80.6 1698.75    89.9  1693.2     103  1691.2
   148.9 1665.16   188.3 1639.51   214.6 1624.41   227.7 1613.09   240.8 1611.01
   253.9 1600.04   270.3 1596.43   286.7 1588.51   316.3 1580.71   391.7 1556.16
   398.3 1551.91   434.4 1553.58   447.5 1552.38   457.4 1549.15     477 1537.48
   486.9  1534.8   578.9 1533.65   588.6 1532.09     605 1533.64   844.6 1538.41
     932 1538.48   989.1  1541.9  1012.1 1545.23  1038.3 1551.97    1132 1586.64
#Mann= 3 ,-1 , 0
       0      .1       0   578.9    .045       0     605      .1       0
#XS Ineff= 2 , 0
                          719.36         1538.31
Permanent Ineff=
       F       F
Bank Sta=578.9,605
XS Rating Curve= 0 ,0
Exp/Cntr=0.3,0.1

Type RM Length L Ch R = 1 ,9840    ,365.5,349.6,342.2
XS GIS Cut Line= 3
     2051092.962      243104.636      2050954.27      243657.457
     2050864.672      244194.549
#Sta/Elev= 30
       0 1729.24    22.4 1731.58    61.5 1723.41    79.9 1714.97    86.7 1707.99
    90.1 1701.98    96.9 1696.06   110.4 1690.14   127.3 1679.18   139.9 1677.81
   154.4 1669.94   171.3 1667.32   198.3  1653.3   245.4 1636.52   259.2 1635.63
   309.9 1622.43   407.6 1565.83     425 1554.04   482.5 1550.16   502.8 1545.24
   516.3 1533.47   529.8 1530.31   540.1  1530.1   550.1 1533.26   560.11531.475
     567 1529.69  575.081531.453   636.9 1534.43  1042.7 1535.82  1114.5 1549.75
#Mann= 7 ,-1 , 0
       0      .1       0     390     .04       0     490      .1       0
   560.1    .045       0  575.08      .1       0  689.95     .05       0
  789.95      .1       0
#XS Ineff= 2 , 0
                          732.05         1536.58
Permanent Ineff=
       F       F
Bank Sta=560.1,575.08
XS Rating Curve= 0 ,0
Exp/Cntr=0.3,0.1

Type RM Length L Ch R = 1 ,9490    ,327.5,336.8,341
XS GIS Cut Line= 3
     2050454.129      243123.742     2050637.061      243648.869
     2050769.148      244196.843
#Sta/Elev= 30
       0 1696.19    75.9 1681.44   104.2 1678.96   193.9  1678.3   263.4 1670.33
   298.1 1662.15   307.7 1658.28   332.9 1644.42   360.7 1626.44   402.3 1596.03
   412.8 1589.48   426.7 1578.34   433.6 1567.83   440.6 1559.21   457.2 1558.12
   461.4 1556.83   480.3 1541.28   490.6 1534.83     517  1531.6   527.4 1529.09
   548.3 1528.21   560.1 1529.47   565.9 1531.49   582.1 1532.28   619.4  1531.2
   703.7 1531.55   737.5 1533.45  1037.8 1533.87  1091.8 1536.69  1119.7 1541.74
#Mann= 5 ,-1 , 0
       0      .1       0     480     .04       0   527.4    .045       0
   560.1     .04       0  586.08      .1       0
#XS Ineff= 2 , 0
                          726.13         1535.29
Permanent Ineff=
       F       F
Bank Sta=527.4,560.1
XS Rating Curve= 0 ,0
Exp/Cntr=0.3,0.1

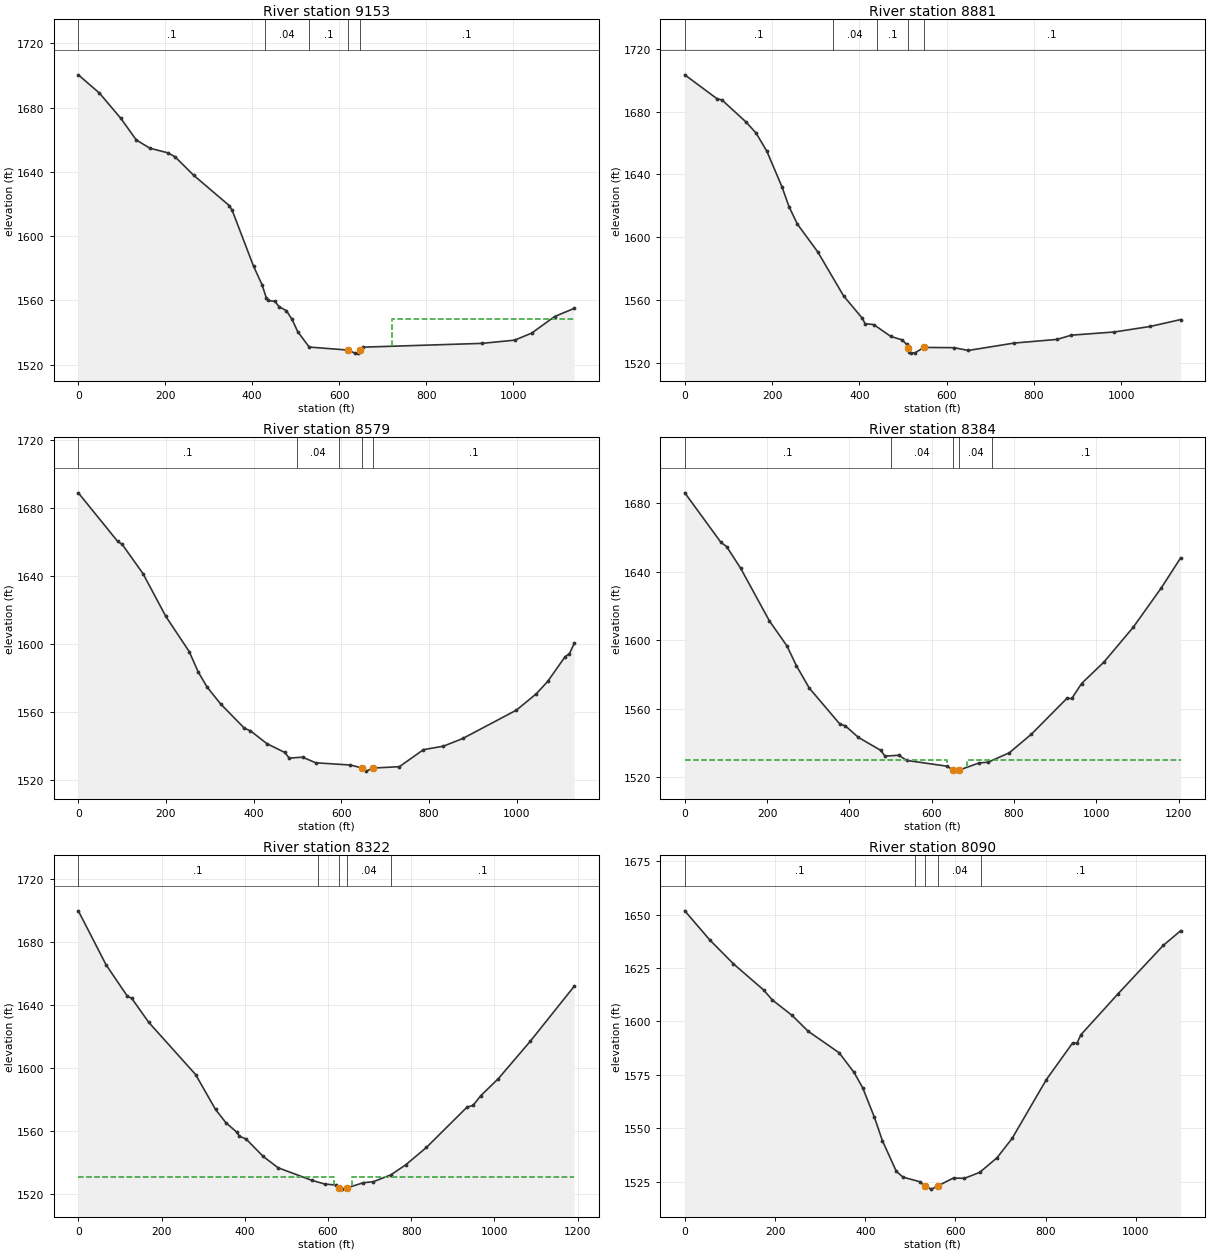
Type RM Length L Ch R = 1 ,9153    ,263.4,272,255.8
XS GIS Cut Line= 2
     2050364.331      243146.787     2050332.134      244286.844
#Sta/Elev= 30
       0 1700.48    48.5 1689.12    97.8 1673.35   133.4 1659.88   164.7 1654.76
   206.1 1651.89   222.5 1649.42   265.1 1637.98   347.2 1619.04   353.9 1616.08
     403 1581.32   422.7  1569.7   432.5 1561.44   435.8 1559.94   452.2 1559.38
   461.9    1556   478.5 1553.61   491.6 1548.17   504.7  1540.5     531 1530.93
   620.7 1529.04     636 1527.15   642.6 1527.17  647.021528.987   653.7 1530.86
   928.1 1533.22  1003.6 1535.23  1042.9 1539.63  1095.5 1549.94  1140.5    1555
#Mann= 5 ,-1 , 0
       0      .1       0     430     .04       0     530      .1       0
   620.7    .045       0  647.02      .1       0
#XS Ineff= 2 , 0
                          722.16         1548.16
Permanent Ineff=
       F       F
Bank Sta=620.7,647.02
XS Rating Curve= 0 ,0
Exp/Cntr=0.3,0.1

Type RM Length L Ch R = 1 ,8881    ,296.4,302.4,298.3
XS GIS Cut Line= 3
     2050116.879      243136.908      2050135.76      243691.753
     2050132.181      244272.405
#Sta/Elev= 30
       0 1703.48    74.8 1688.05    84.7 1687.58   140.5 1673.36   163.5 1666.29
     188 1654.79   222.6 1632.12   238.7 1619.54   257.8 1608.41   304.6 1590.67
   363.7 1562.67   406.4 1548.47     413 1544.93   432.7 1544.37     472 1536.81
   498.3 1534.58   508.2 1531.68   511.1 1529.29   514.7 1526.63     518 1526.18
   527.9 1526.44   547.5 1529.81   616.5 1529.66   649.3 1527.88   754.2 1532.59
   852.7 1534.92   885.5 1537.63   983.9 1539.65  1065.9 1543.17  1135.8 1547.55
#Mann= 5 ,-1 , 0
       0      .1       0     340     .04       0     440      .1       0
   511.1    .045       0   547.5      .1       0
Bank Sta=511.1,547.5
XS Rating Curve= 0 ,0
Exp/Cntr=0.3,0.1

Type RM Length L Ch R = 1 ,8579    ,164.6,195.2,219.9
XS GIS Cut Line= 4
2049998.64857146243098.9661622812049861.35693744243594.741507345
2049830.84768543243955.7676560572049815.59305943244210.011422757
#Sta/Elev= 30
       0 1688.77    89.7 1660.28     100 1658.56   147.6 1641.34   199.7 1616.24
   253.1 1595.56   273.6 1583.62     294 1574.73   324.6 1564.91   379.1 1550.56
   392.7 1549.13   430.2 1541.57     471 1536.41   481.2 1533.09   511.9 1533.63
   541.6 1530.34   620.7 1529.03     647 1527.34   656.8 1525.44   672.1 1527.24
   732.6 1528.05   787.5 1538.03   833.1 1540.08   877.4 1544.61   999.6 1561.23
  1045.1 1570.86  1071.3 1578.18  1110.8 1592.64  1120.6 1594.39  1131.4 1600.35
#Mann= 5 ,-1 , 0
       0      .1       0     500     .04       0  594.43      .1       0
     647    .045       0   672.1      .1       0
Bank Sta=647,672.1
XS Rating Curve= 0 ,0
Exp/Cntr(USF)=0,0
Exp/Cntr=0.5,0.3

Type RM Length L Ch R = 1 ,8384    ,63.3,61.8,58.7
XS GIS Cut Line= 5
2049981.13337757243097.3190642992049838.03032176243614.739132401
2049744.99734596243637.5915671252049646.12162565243667.502018933
     2049388.476      244059.152
#Sta/Elev= 30
       0 1686.01      88 1657.02   101.5 1654.68   135.7 1641.99   205.5 1611.27
   248.2 1596.65   271.2 1585.09   302.5 1572.02   377.4 1550.85   389.5 1550.11
   421.5  1543.3   476.1 1535.68   486.3 1532.31   520.3 1532.83   538.9 1529.81
   637.8 1526.42 650.6151524.227   657.4 1523.56 667.3151524.232   715.4 1528.38
   736.4 1528.72   788.5 1534.27   842.3 1545.18   928.2 1565.99   940.4 1565.99
     964 1574.71  1018.2 1587.17  1089.7  1607.6    1158 1630.61  1204.7 1648.04
#Mann= 5 ,-1 , 0
       0      .1       0     500     .04       0 650.615    .045       0
 667.315     .04       0  745.94      .1       0
#XS Ineff= 2 , 0
          637.11 1530.22  684.57         1530.28
Permanent Ineff=
       F       F
Bank Sta=650.615,667.315
XS Rating Curve= 0 ,0
Exp/Cntr=0.5,0.3

Type RM Length L Ch R = 1 ,8322    ,248,232.4,216.1
XS GIS Cut Line= 5
2049947.24156129243068.9341715072049808.59723838243544.809818418
2049646.18653873243613.1377693632049495.54209837243794.961431861
 2049320.4194543 244018.40268817
#Sta/Elev= 30
       0 1700.08    66.7 1665.76   117.9 1645.82   128.2 1644.52   169.2 1629.23
     282 1595.99   329.8 1573.83     355 1565.32   381.1 1559.36   387.4 1556.79
   403.3 1555.05   444.4 1543.96   480.2 1536.77     561 1528.81   592.7  1526.4
   618.9  1525.8 626.5231524.055   633.2 1523.19 646.2221523.995   685.3 1527.28
   708.5 1527.86   751.3 1532.26   787.8  1538.8   836.8  1549.7   934.7 1575.39
   948.7 1576.35   967.4 1582.58  1009.5 1593.36  1086.6 1617.24  1191.9  1652.1
#Mann= 5 ,-1 , 0
       0      .1       0  575.66     .04       0 626.523    .045       0
 646.222     .04       0  751.86      .1       0
#XS Ineff= 2 ,-1
       0  615.18 1530.66  658.361191.872 1530.81
Permanent Ineff=
       F       F
Bank Sta=626.523,646.222
XS Rating Curve= 0 ,0
Exp/Cntr=0.5,0.3

Type RM Length L Ch R = 1 ,8090    ,341.2,350,357.2
XS GIS Cut Line= 3
     2049739.993      242995.308     2049482.355      243477.315
     2049221.287       243964.19
#Sta/Elev= 30
       0 1651.84    55.6 1638.15   107.7 1627.03   174.7 1614.77   193.7 1610.14
   237.9 1602.84   273.6 1595.41   342.1 1585.34     375 1576.19   394.2 1568.98
   420.2 1555.17     438 1544.17   468.6 1529.91   483.4  1527.1   520.7 1524.95
   531.8 1522.88   546.7 1521.47   561.4 1523.04   595.6  1526.7   619.8 1526.52
   653.7 1529.33   691.9 1536.14   725.4 1545.19   801.5 1572.82   859.4 1589.87
   869.4 1589.88     878 1593.81   959.9 1612.88  1060.4 1635.63    1099 1642.52
#Mann= 5 ,-1 , 0
       0      .1       0     510     .04       0   531.8    .045       0
   561.4     .04       0  656.54      .1       0
Bank Sta=531.8,561.4
XS Rating Curve= 0 ,0
Exp/Cntr=0.3,0.1