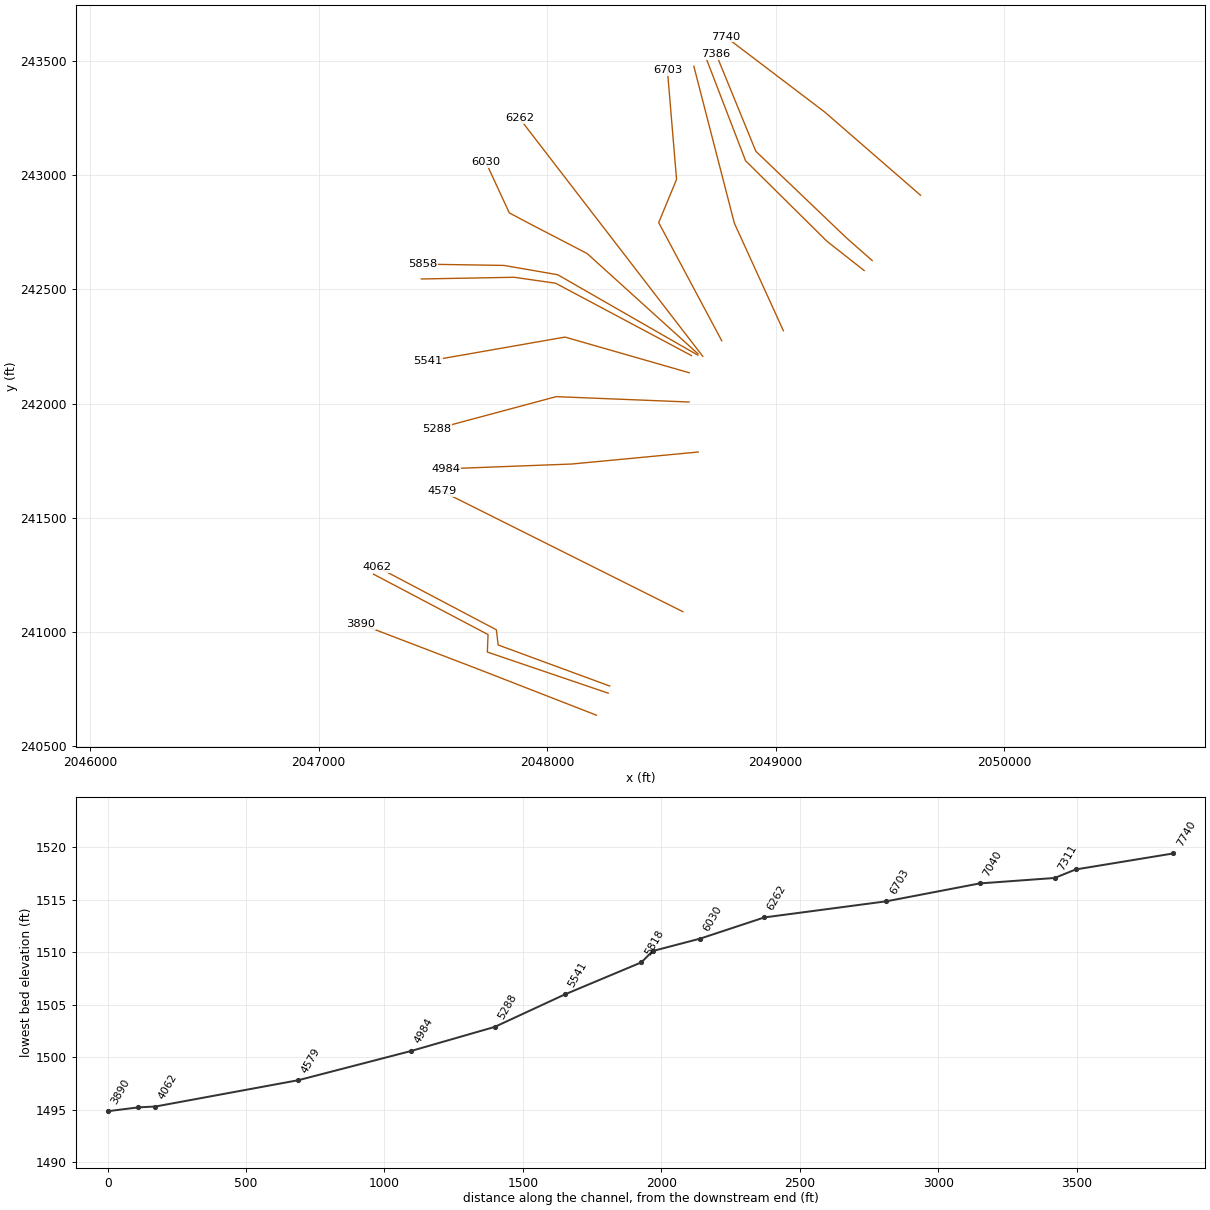
HEC-RAS study KELLYCK.prj: KELLYCK

--- KELLYCK.g01 (geometry) --- (continued)

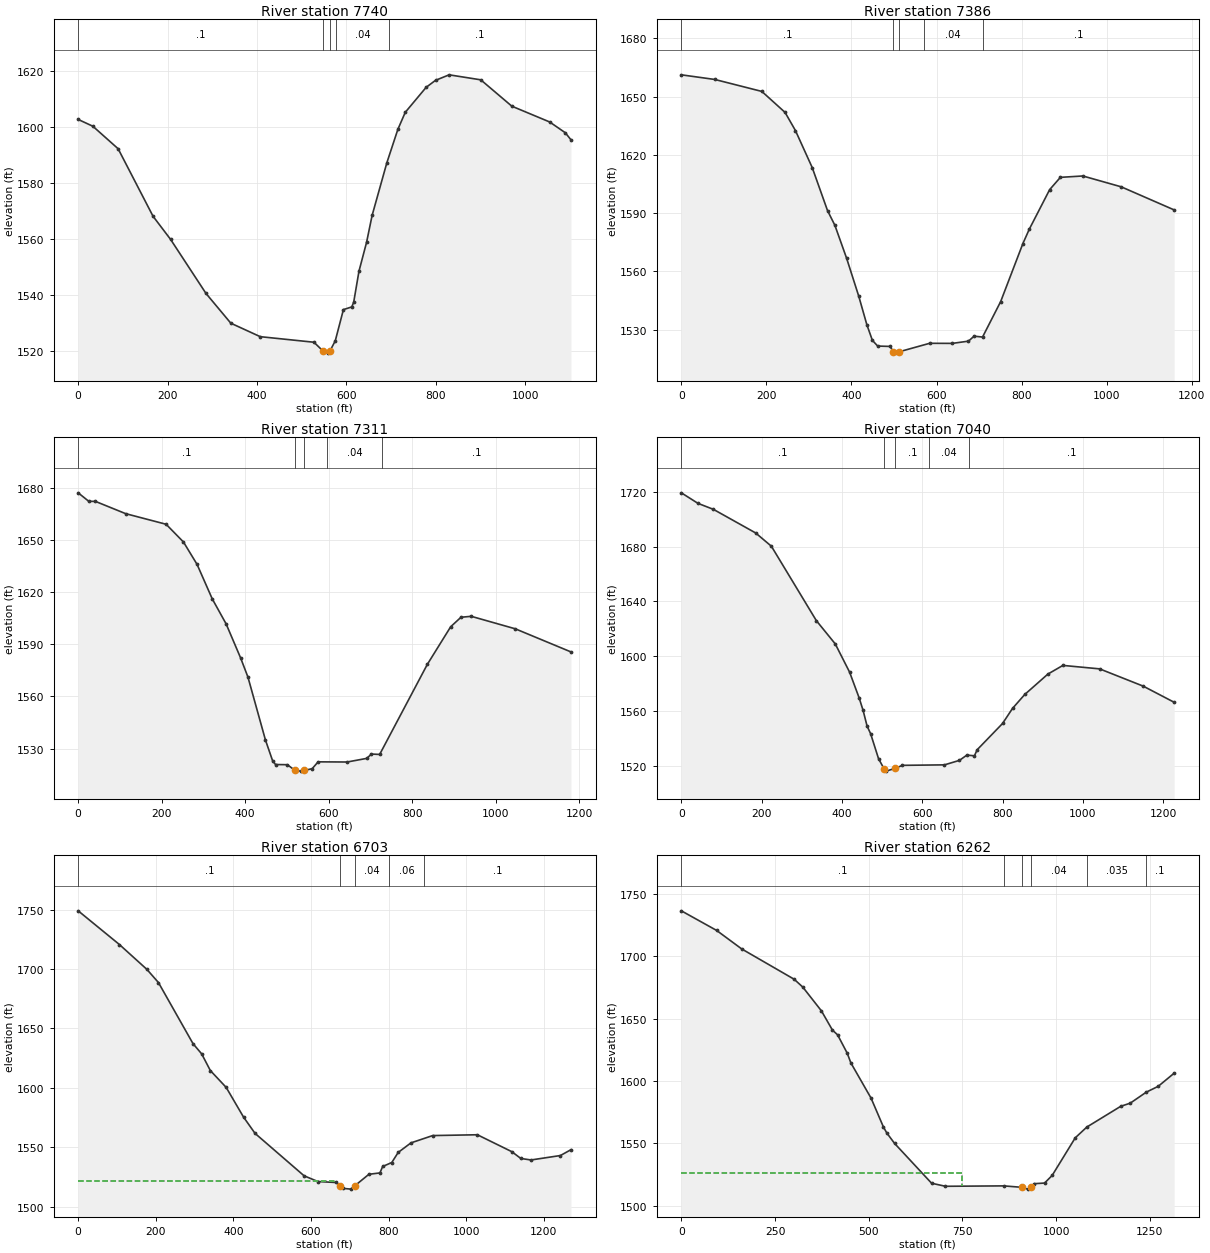
Type RM Length L Ch R = 1 ,7740    ,352.7,353.3,349.6
XS GIS Cut Line= 3
     2049634.466      242911.841     2049214.763      243276.397
     2048779.629      243606.642
#Sta/Elev= 30
       0 1602.64    32.8 1600.22    89.3 1592.21   167.5 1568.14   206.7 1559.91
   285.9 1540.66   341.4 1530.07   407.2 1525.27   527.3 1523.29   548.41520.038
     558 1519.41   563.41520.258     575  1523.8   593.2 1534.91   611.9 1535.87
   616.2 1537.54     628 1548.59     645 1558.87   657.4 1568.46   690.3 1587.18
   714.9 1599.07   731.5 1605.17   778.2 1614.07   799.2 1616.57   829.7 1618.53
   900.4 1616.75   969.9 1607.36  1054.5 1601.74  1089.3 1597.92  1102.2 1595.39
#Mann= 5 ,-1 , 0
       0      .1       0   548.4    .045       0   563.4      .1       0
  575.92     .04       0  695.92      .1       0
Bank Sta=548.4,563.4
XS Rating Curve= 0 ,0
Exp/Cntr=0.5,0.3

Type RM Length L Ch R = 1 ,7386    ,67.5,75.9,88.7
XS GIS Cut Line= 4
2049422.77071868242626.2161439742049310.27171142  242725.0972156
2048913.66399753243104.1891314062048739.51725246243530.205974676
#Sta/Elev= 30
       0 1661.23    78.7 1658.84   189.3 1652.68   243.9 1641.87   268.3 1632.52
   307.7 1613.48   343.7 1591.31   361.1 1583.68   388.7 1566.68   417.2 1547.16
   436.2 1532.51   449.2 1524.45   461.7 1521.52     491 1521.33 498.0561518.649
   502.6 1517.88 512.1451518.574   583.8 1522.94   637.2  1522.9   675.1 1524.05
   688.3 1526.61   708.2 1526.16   750.8 1544.42   803.1 1574.34   818.2 1581.76
     866 1602.09   891.2 1608.42     944 1609.13  1034.3 1603.54  1158.7 1591.65
#Mann= 5 ,-1 , 0
       0      .1       0 498.056    .045       0 512.145      .1       0
  569.78     .04       0  708.42      .1       0
Bank Sta=498.056,512.145
XS Rating Curve= 0 ,0
Exp/Cntr(USF)=0,0
Exp/Cntr=0.5,0.3

Type RM Length L Ch R = 1 ,7311    ,284.2,271,238.9
XS GIS Cut Line= 4
2049387.54076977242582.5058145182049225.19497784 242710.08367438
2048868.62337387243062.9018930512048699.15266908 243503.55284921
#Sta/Elev= 30
       0 1677.05    25.4 1672.17    41.3 1672.13   113.9 1665.06   210.6 1658.98
   252.2 1648.76   284.7 1635.92     321 1616.13   354.3  1601.7   389.1 1582.08
   406.6 1571.09   448.5 1534.94   465.6 1523.03   472.6 1520.87     501 1520.76
   519.1 1517.52   532.5 1517.07 541.8231517.453   560.5  1518.5   574.6 1522.41
   644.1 1522.31   691.1  1524.4   702.2 1526.88     722 1526.67   836.2 1578.46
   892.1 1600.07   916.7 1605.52   941.3 1606.06  1046.8 1598.88  1180.2 1585.59
#Mann= 5 ,-1 , 0
       0      .1       0   519.1    .045       0 541.823      .1       0
  596.48     .04       0   728.1      .1       0
Bank Sta=519.1,541.823
XS Rating Curve= 0 ,0
Exp/Cntr(USF)=0,0
Exp/Cntr=0.5,0.3

Type RM Length L Ch R = 1 ,7040    ,349.3,336.3,315.2
XS GIS Cut Line= 3
     2049034.182      242318.756     2048819.656      242789.217
      2048642.16      243476.566
#Sta/Elev= 30
       0 1719.06    41.5 1711.39    79.9 1707.03   185.1 1689.85   224.2  1680.2
   336.2 1626.04   383.3  1609.1   418.9  1588.6   442.7 1569.84   452.6  1560.7
   462.5  1549.3   471.2 1543.85     491 1525.62   505.4 1517.89     509 1516.55
   533.2 1518.58   550.2 1520.76   655.2 1521.11   692.5 1524.39   710.9 1528.21
   729.8  1527.7   736.5 1532.09   799.8 1551.23   824.6  1562.2   855.1 1572.34
   912.7 1587.18     950 1593.48  1041.5 1590.96  1150.1 1578.38    1227 1566.65
#Mann= 5 ,-1 , 0
       0      .1       0   505.4    .045       0   533.2      .1       0
  617.06     .04       0  717.06      .1       0
Bank Sta=505.4,533.2
XS Rating Curve= 0 ,0
Exp/Cntr=0.3,0.1

Type RM Length L Ch R = 1 ,6703    ,413.3,441.6,463.6
XS GIS Cut Line= 4
     2048764.426      242274.691     2048488.384      242792.053
     2048566.509      242981.288     2048526.578      243458.719
#Sta/Elev= 30
       0    1749   106.4 1720.61     177 1699.77   206.8 1688.69     296 1637.23
   318.3 1628.64   340.6 1614.64   381.5 1600.42   426.2 1575.46   455.9 1561.74
   582.3 1526.05     618 1521.22   664.2 1520.44     676 1517.76   681.9  1515.5
   703.2 1514.85   713.4 1517.77   749.3 1527.33   777.7 1528.49   784.8  1533.9
   808.3 1537.24   824.8 1545.72   857.7 1553.76   913.7 1559.91  1028.9 1560.59
  1117.8 1546.34  1140.9 1540.64  1167.2 1539.38  1242.9 1543.12  1270.2 1548.04
#Mann= 5 ,-1 , 0
       0      .1       0     676    .045       0   713.4     .04       0
  801.13     .06       0  891.13      .1       0
#XS Ineff= 2 , 0
          660.15 1521.49
Permanent Ineff=
       F       F
Bank Sta=676,713.4
XS Rating Curve= 0 ,0
Exp/Cntr=0.3,0.1

Type RM Length L Ch R = 1 ,6262    ,221,231.8,240.1
XS GIS Cut Line= 2
     2048681.093      242206.983     2047879.009       243248.65
#Sta/Elev= 30
       0  1736.5    94.1 1720.79   161.1 1705.93     301 1681.63     324 1675.34
   373.7 1656.27   403.1 1640.85   416.9 1637.04   442.6  1622.3   452.3 1614.53
   506.2 1586.25   539.3 1563.02   548.3 1558.27   568.9 1549.96   667.6 1518.04
   704.6 1515.59   860.2 1515.91   908.2 1514.77   924.8 1513.31   932.7 1514.71
   940.9 1517.66     969 1518.18   989.3  1524.3  1050.9 1554.46  1081.7 1563.08
  1172.1 1579.71  1197.7 1582.27  1240.4 1591.08  1272.2 1595.76  1314.7 1606.28
#Mann= 6 ,-1 , 0
       0      .1       0   860.2     .04       0   908.2    .045       0
   932.7     .04       0  1081.7    .035       0  1240.4      .1       0
#XS Ineff= 2 , 0
             750 1525.89
Permanent Ineff=
       F       F
Bank Sta=908.2,932.7
XS Rating Curve= 0 ,0
Exp/Cntr=0.3,0.1

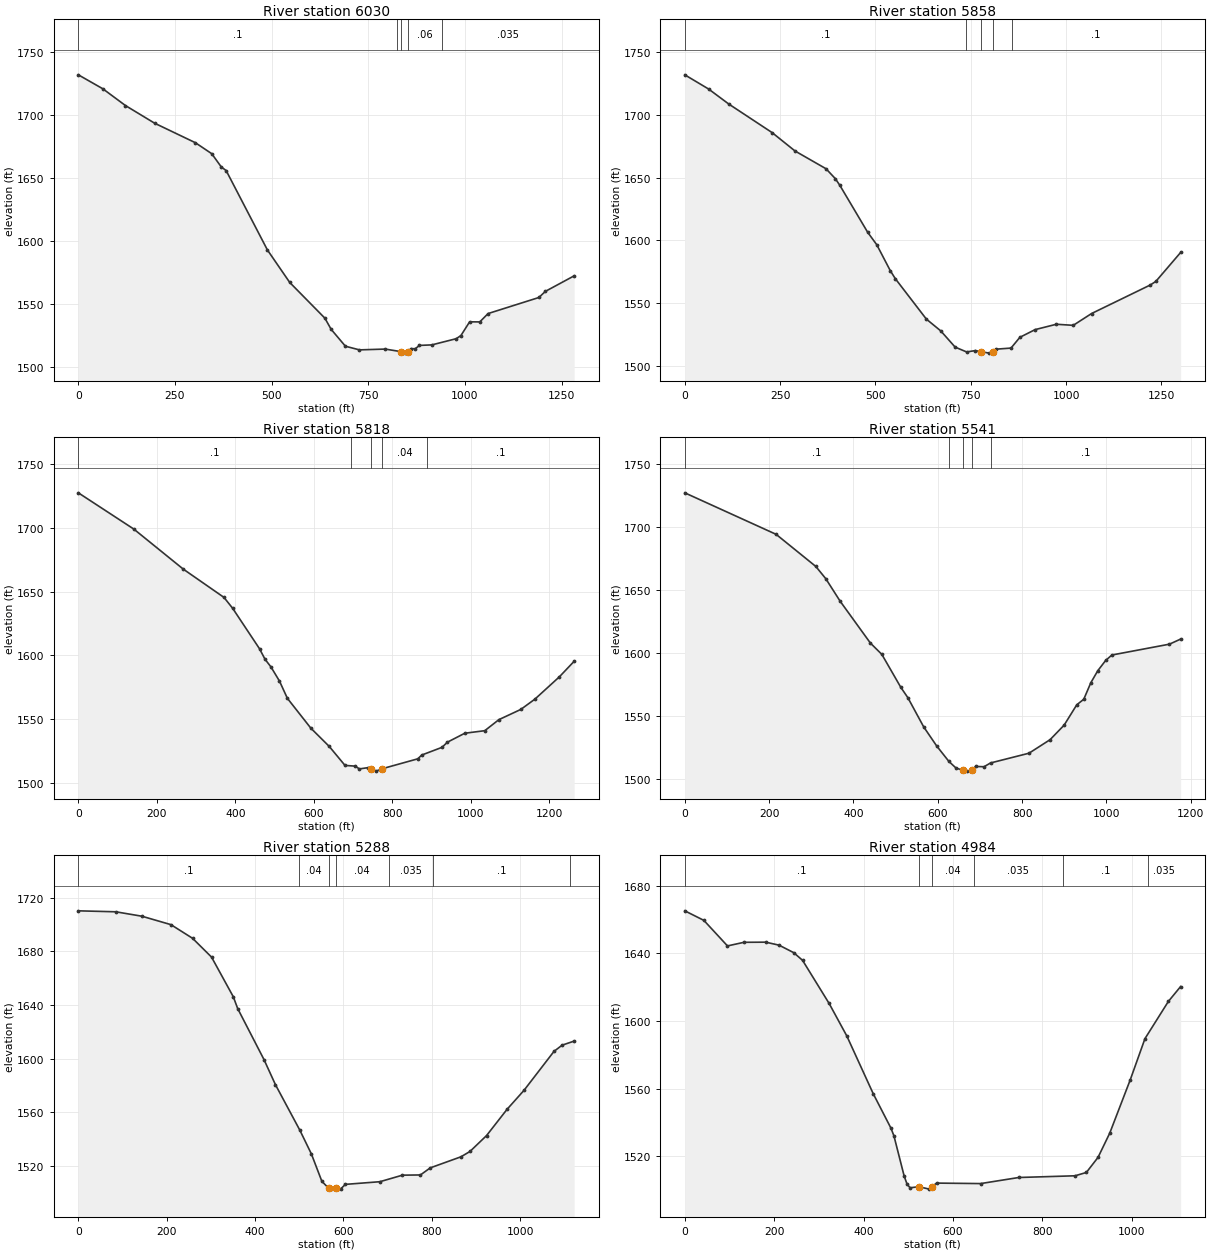
Type RM Length L Ch R = 1 ,6030    ,163.3,171.3,178.7
XS GIS Cut Line= 5
2048660.27778399242217.7753100522048174.83995121242656.921390739
2047938.37667699242779.5319773692047834.53301689242834.581628509
2047731.94048522243056.031361505
#Sta/Elev= 30
       0 1731.89    63.3 1720.84     122 1707.52   197.4 1693.54     303 1678.04
   345.1 1669.37   369.9 1658.81   382.3 1656.04   489.1 1593.07   546.9  1567.3
   637.8 1538.99     654 1530.15   690.9 1516.76   727.2 1513.87   793.8  1514.5
   833.5 1512.54   843.8 1511.29   853.6  1512.4   860.3 1514.84   871.4 1514.76
   882.5 1517.41   914.4 1517.82   977.5 1522.73   989.7 1525.23  1012.2  1536.1
  1038.5 1536.04    1060 1542.66  1191.4 1555.39  1208.2 1560.25  1282.6 1572.56
#Mann= 5 ,-1 , 0
       0      .1       0   824.6     .06       0   833.5    .045       0
   853.6     .06       0  940.96    .035       0
Bank Sta=833.5,853.6
XS Rating Curve= 0 ,0
Exp/Cntr(USF)=0,0
Exp/Cntr=0.5,0.3

Type RM Length L Ch R = 1 ,5858    ,40.4,40.8,41.5
XS GIS Cut Line= 4
2048659.80598089242211.7647413212048046.31831429242563.917782576
2047810.93180776242604.6933978792047456.92532945242610.253709057
#Sta/Elev= 30
       0 1732.03    62.3 1720.74   115.3 1708.75   229.2 1685.91     289 1671.31
   370.3 1657.15   394.8 1649.23   406.6  1643.9   479.6 1606.47   503.5  1596.5
     539  1575.8   552.1 1569.48   633.5 1537.24   671.2 1527.85     709  1514.9
     739 1511.06   762.3 1512.14     776 1511.24   798.9 1510.11  807.781511.295
   815.5 1513.24   855.5 1514.14   878.8 1522.74   918.8 1528.87   974.5 1533.13
  1018.7 1532.27  1066.8 1541.69    1221 1564.48  1235.4 1567.33  1300.3 1590.37
#Mann= 5 ,-1 , 0
       0      .1       0  737.37     .04       0     776    .045       0
  807.78     .04       0  857.37      .1       0
#XS Ineff= 2 , 0
          766.18 1511.16  813.55         1511.31
Permanent Ineff=
       F       F
Bank Sta=776,807.78
XS Rating Curve= 0 ,0
Exp/Cntr(USF)=0,0
Exp/Cntr=0.5,0.3

Type RM Length L Ch R = 1 ,5818    ,268.5,276.9,283.6
XS GIS Cut Line= 4
  2048632.004425242209.9113042622048037.05112899242526.849041391
2047855.41429718242552.7971602212047449.51158121242545.383411984
#Sta/Elev= 30
       0 1727.46   141.3 1699.03   267.6 1667.54   371.2 1645.37   393.2 1636.86
   461.7  1605.1   475.8 1596.83   490.8 1590.86   512.6 1579.72   532.7  1566.2
   592.6 1542.73   639.4 1528.43   679.6 1513.52   706.1 1512.94   716.1 1510.77
   739.1 1511.79   745.9 1510.67   759.1 1509.03   774.3 1510.91   865.1 1518.69
   875.2 1521.66   926.8  1527.7   940.6 1531.75     985 1538.78  1035.8 1540.77
  1071.9 1549.46  1127.6 1557.45  1163.7 1565.57  1226.1 1583.09  1263.6 1595.25
#Mann= 5 ,-1 , 0
       0      .1       0  694.11     .04       0   745.9    .045       0
   774.3     .04       0  887.59      .1       0
#XS Ineff= 2 , 0
          740.06 1510.62  778.58         1510.76
Permanent Ineff=
       F       F
Bank Sta=745.9,774.3
XS Rating Curve= 0 ,0
Exp/Cntr(USF)=0,0
Exp/Cntr=0.5,0.3

Type RM Length L Ch R = 1 ,5541    ,257.3,253.1,253
XS GIS Cut Line= 3
 2048622.0612022242134.8980506332048078.16271635242291.005588711
2047477.27258963242185.694947944
#Sta/Elev= 30
       0 1727.13   216.6 1694.14   310.8  1668.6   334.4 1658.88   368.5 1640.96
   440.2 1607.72   467.3 1598.74   512.3 1572.56     529 1564.34   566.5 1541.16
   597.4 1525.95   626.4 1513.66   643.1 1508.46   658.81506.703   669.7 1505.97
   680.21506.706   689.7 1509.69   709.7 1509.46     725 1512.45   816.3 1520.21
   866.3 1530.96   899.6 1542.51   929.6 1558.68   946.2 1563.09   962.9 1576.18
   979.5  1585.8   998.2 1593.95  1012.8 1598.24  1149.4 1606.86  1175.9  1610.9
#Mann= 5 ,-1 , 0
       0      .1       0   626.4     .04       0   658.8    .045       0
   680.2     .04       0     725      .1       0
Bank Sta=658.8,680.2
XS Rating Curve= 0 ,0
Exp/Cntr(USF)=0,0
Exp/Cntr=0.3,0.1

Type RM Length L Ch R = 1 ,5288    ,301.9,303.2,301.4
XS GIS Cut Line= 3
     2048621.597      242006.769     2048039.515      242030.274
     2047518.395      241890.461
#Sta/Elev= 30
       0 1710.22    84.8  1709.5   143.9  1706.2   209.6 1699.92   258.6 1689.73
   301.5 1675.73   350.8 1646.14   360.6 1637.42   420.1 1599.44     446 1580.76
   501.5 1546.66   527.4 1529.11   551.1 1508.73   566.21503.619   570.8 1502.88
   582.6 1503.77   594.1 1503.13   604.3 1506.42   682.5 1508.41   733.4 1513.28
   774.2 1513.44   796.5 1518.73   865.9 1526.96   886.3 1530.94   923.8 1542.76
   970.2 1562.32  1008.6 1576.48  1076.5 1605.53  1094.9 1610.14  1122.1 1613.17
#Mann= 7 ,-1 , 0
       0      .1       0     500     .04       0   566.2    .045       0
   582.6     .04       0  702.56    .035       0  802.56      .1       0
 1112.56    .035       0
Bank Sta=566.2,582.6
XS Rating Curve= 0 ,0
Exp/Cntr=0.3,0.1

Type RM Length L Ch R = 1 ,4984    ,417.8,405.4,391.9
XS GIS Cut Line= 3
     2048661.418      241787.9162048107.43879743241735.339405138
     2047554.897       241714.36
#Sta/Elev= 30
       0 1665.21    42.7 1659.56    95.5 1644.45   132.4 1646.59   181.1 1646.67
     211 1644.89   243.8 1640.45   263.5 1635.92   322.9 1610.43   362.4 1591.24
   421.7 1556.97   461.3 1536.62   467.9 1532.12   490.9 1508.23   497.5 1503.41
   504.1 1501.38   523.9    1502     547 1500.58  552.821502.061   563.4 1504.15
   661.9 1503.86   747.3 1507.46   873.2 1508.47   898.5 1510.44   924.6 1519.36
   950.8 1533.69   996.8 1565.32  1029.6  1589.6  1081.9 1611.58  1109.4 1620.43
#Mann= 6 ,-1 , 0
       0      .1       0   523.9    .045       0  552.82     .04       0
  646.47    .035       0  846.47      .1       0 1036.47    .035       0
Bank Sta=523.9,552.82
XS Rating Curve= 0 ,0
Exp/Cntr=0.3,0.1

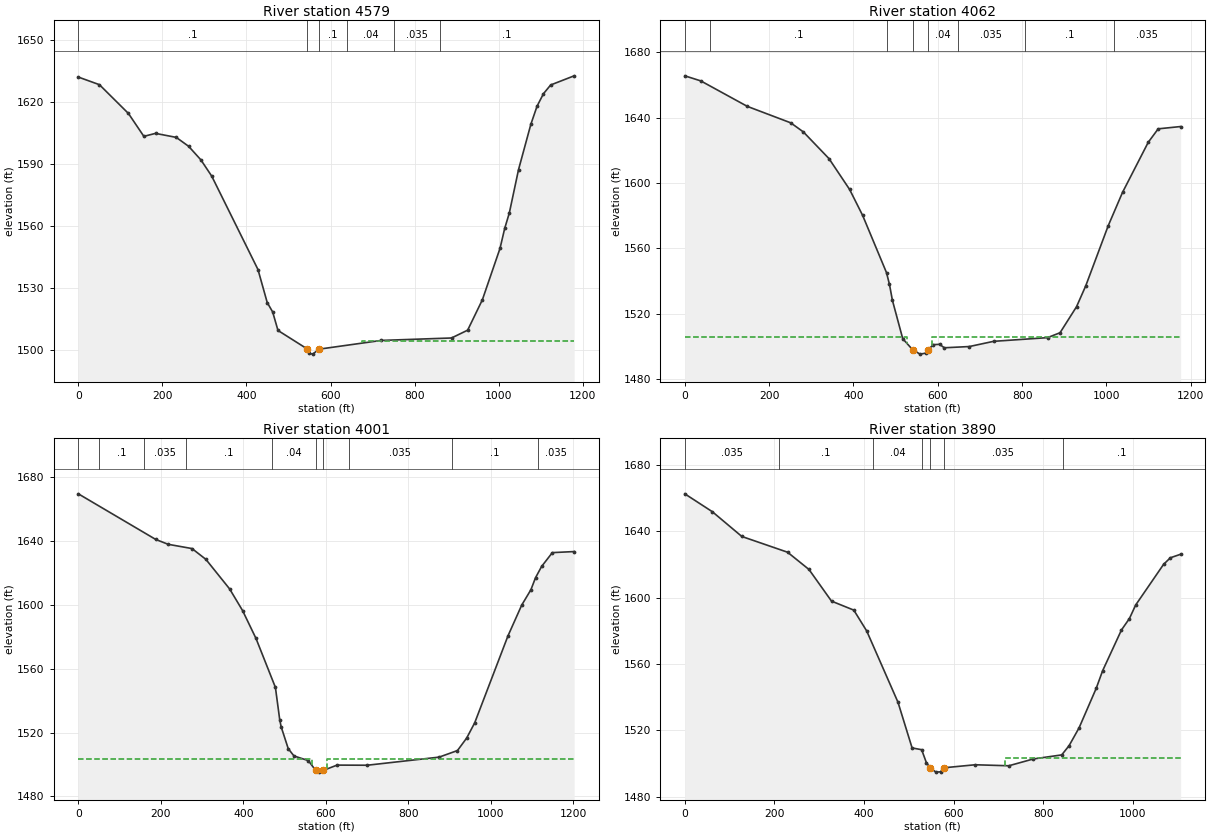
Type RM Length L Ch R = 1 ,4579    ,536.1,516.6,482.6
XS GIS Cut Line= 2
     2048594.287      241088.927     2047539.201      241616.502
#Sta/Elev= 30
       0 1632.22    50.2 1628.52   119.2 1614.56   155.9 1603.46   183.6  1604.9
   232.9 1602.96   262.3 1598.65   291.6 1592.04   317.3 1584.18   427.4 1538.84
   449.4 1522.82   462.3 1518.28     475 1509.29   544.2 1500.37   549.1 1498.19
   557.7 1497.81   572.4 1500.21   720.8 1504.46   887.8 1505.64   926.2 1509.43
   961.2 1524.15  1003.3 1549.17  1014.3 1558.76  1025.3 1566.24  1047.3 1587.35
  1076.6 1609.32  1091.3 1618.08  1106.6 1624.16  1123.7 1628.38  1179.6 1632.82
#Mann= 6 ,-1 , 0
       0      .1       0   544.2    .045       0   572.4      .1       0
     640     .04       0     750    .035       0     860      .1       0
#XS Ineff= 2 , 0
                          675.18         1504.08
Permanent Ineff=
       F       F
Bank Sta=544.2,572.4
XS Rating Curve= 0 ,0
Exp/Cntr=0.5,0.3

Type RM Length L Ch R = 1 ,4062    ,59.1,61.3,50
XS GIS Cut Line= 4
     2048273.892      240763.579     2047785.611      240943.267
     2047777.799      241009.673     2047256.965      241284.413
#Sta/Elev= 30
       0 1665.63    37.9 1662.53   148.3 1646.93   251.2 1636.87   281.2  1631.3
   342.1 1614.93   390.9 1596.09   421.8  1580.2   478.4 1545.17   485.4 1538.01
   492.4 1528.25   516.9 1504.74   540.5 1497.96     558  1495.3   571.2 1495.89
     577 1497.96   589.5  1501.1   604.4 1501.29   615.5 1499.19   674.8 1499.94
   732.4 1503.13   860.3 1505.39     890 1508.39   929.1 1524.31     951 1537.11
  1004.4 1573.97  1038.2 1594.29  1099.1 1624.91  1122.8 1633.19    1176 1634.59
#Mann= 8 ,-1 , 0
       0    .035       0      60      .1       0     480     .04       0
   540.5    .045       0     577     .04       0  647.16    .035       0
  807.16      .1       0 1017.16    .035       0
#XS Ineff= 2 , 0
          528.08 1505.92  586.33         1505.61
Permanent Ineff=
       F       F
Bank Sta=540.5,577
XS Rating Curve= 0 ,0
Exp/Cntr=0.5,0.3

Type RM Length L Ch R = 1 ,4001    ,85.1,111.4,149.4
XS GIS Cut Line= 4
     2048267.382      240732.3292047738.38160466240912.260015517
      2047741.34       240988.84     2047240.038      241253.163
#Sta/Elev= 30
       0 1669.51   187.7 1640.93   217.9 1637.89   275.6 1635.23   309.2 1628.48
   366.9 1609.92   398.1 1596.44   430.8 1578.91   477.8 1548.29   488.2 1528.16
   491.6 1523.72   508.9 1509.92   522.8 1505.35   557.5 1502.44 575.3441496.365
   584.6 1495.22   594.21496.333   627.3 1499.62   700.4 1499.54   874.7 1504.61
   919.2 1508.74   941.5 1516.55     961  1526.1  1041.6 1580.53    1075 1599.84
  1097.3 1609.48  1108.4 1616.95  1123.2 1624.03  1149.2 1632.69  1202.1 1633.35
#Mann= 10 ,-1 , 0
       0    .035       0      50      .1       0     160    .035       0
     260      .1       0     470     .04       0 575.344    .045       0
   594.2     .04       0   655.4    .035       0   905.4      .1       0
  1115.4    .035       0
#XS Ineff= 2 , 0
          566.32 1503.36  602.08         1503.42
Permanent Ineff=
       F       F
Bank Sta=575.344,594.2
XS Rating Curve= 0 ,0
Exp/Cntr=0.5,0.3

Type RM Length L Ch R = 1 ,3890    ,329.4,330.8,333
XS GIS Cut Line= 3
     2048215.833      240635.921     2047690.615      240840.518
     2047183.323      241034.656
#Sta/Elev= 30
       0 1662.66    61.5 1651.87   127.3 1636.95   229.4 1627.45   277.2 1617.05
   327.5 1597.96   377.3 1592.53   406.1 1579.94   475.9 1536.98   507.4 1509.43
   528.7 1508.38   539.2 1500.61     548 1497.36   560.6 1494.85   570.9 1495.03
   577.9 1497.46   648.2 1499.29   723.2 1498.68   778.2  1502.8   841.4 1505.24
   857.9 1510.84   880.1 1521.54   918.4  1545.4   932.7    1556   974.7 1580.55
   992.5 1587.46  1006.5 1595.64  1068.7 1620.11  1083.8 1624.09  1106.8 1626.22
#Mann= 7 ,-1 , 0
       0    .035       0     210      .1       0     420     .04       0
     530    .035       0     548    .045       0   577.9    .035       0
  843.66      .1       0
#XS Ineff= 2 , 0
                          714.79         1503.48
Permanent Ineff=
       F       F
Bank Sta=548,577.9
XS Rating Curve= 0 ,0
Exp/Cntr=0.3,0.1