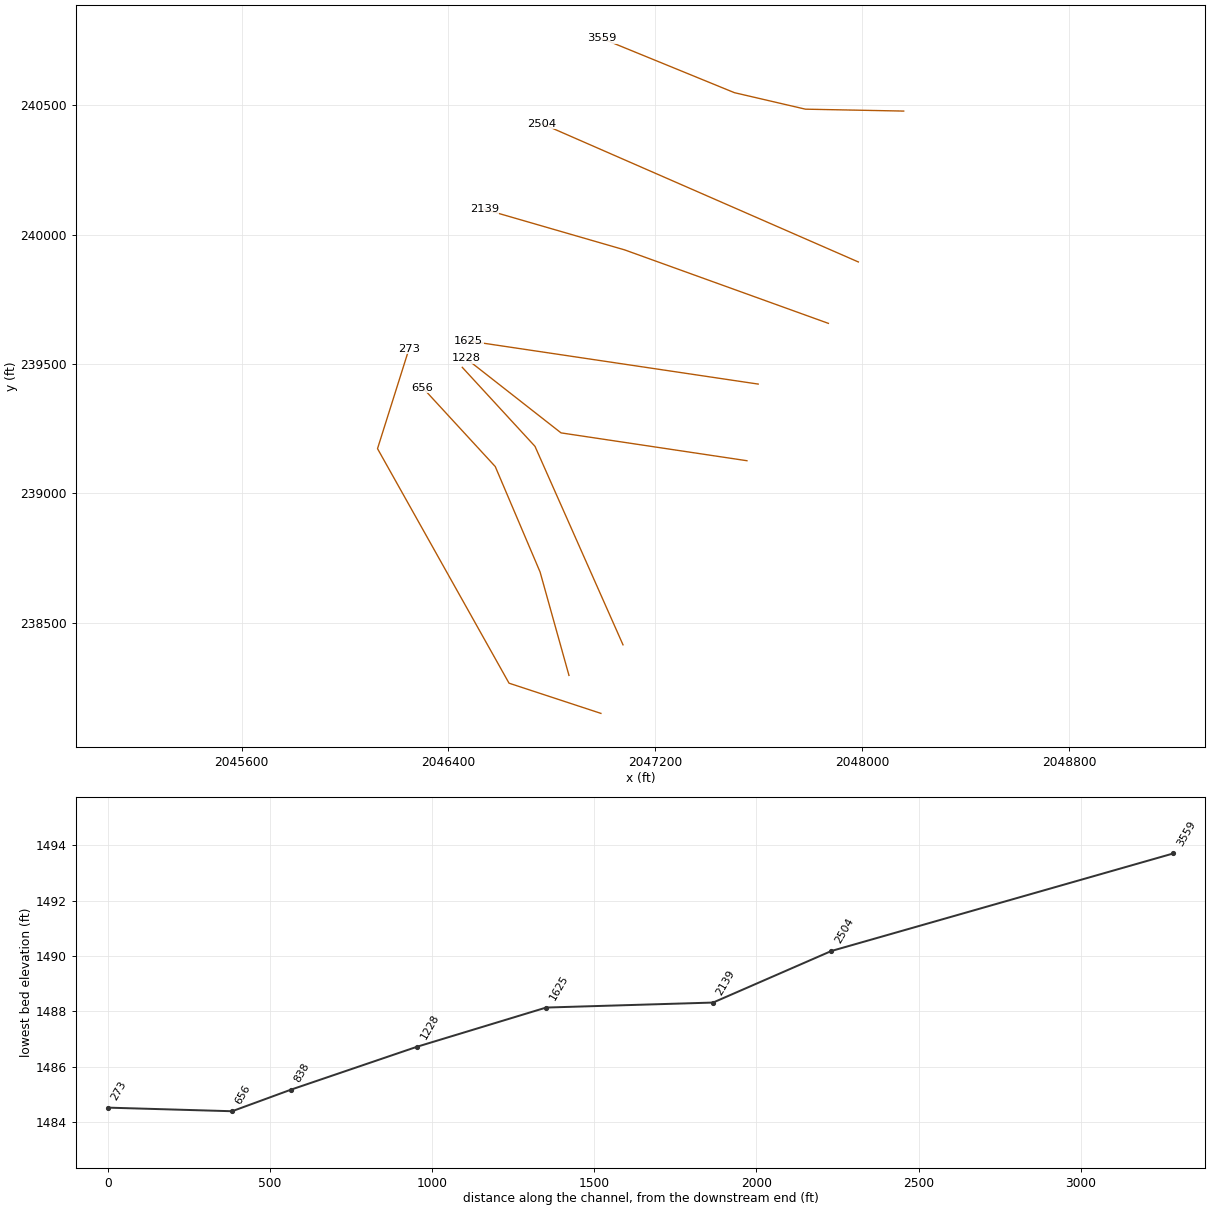
HEC-RAS study KELLYCK.prj: KELLYCK

--- KELLYCK.g01 (geometry) --- (continued)

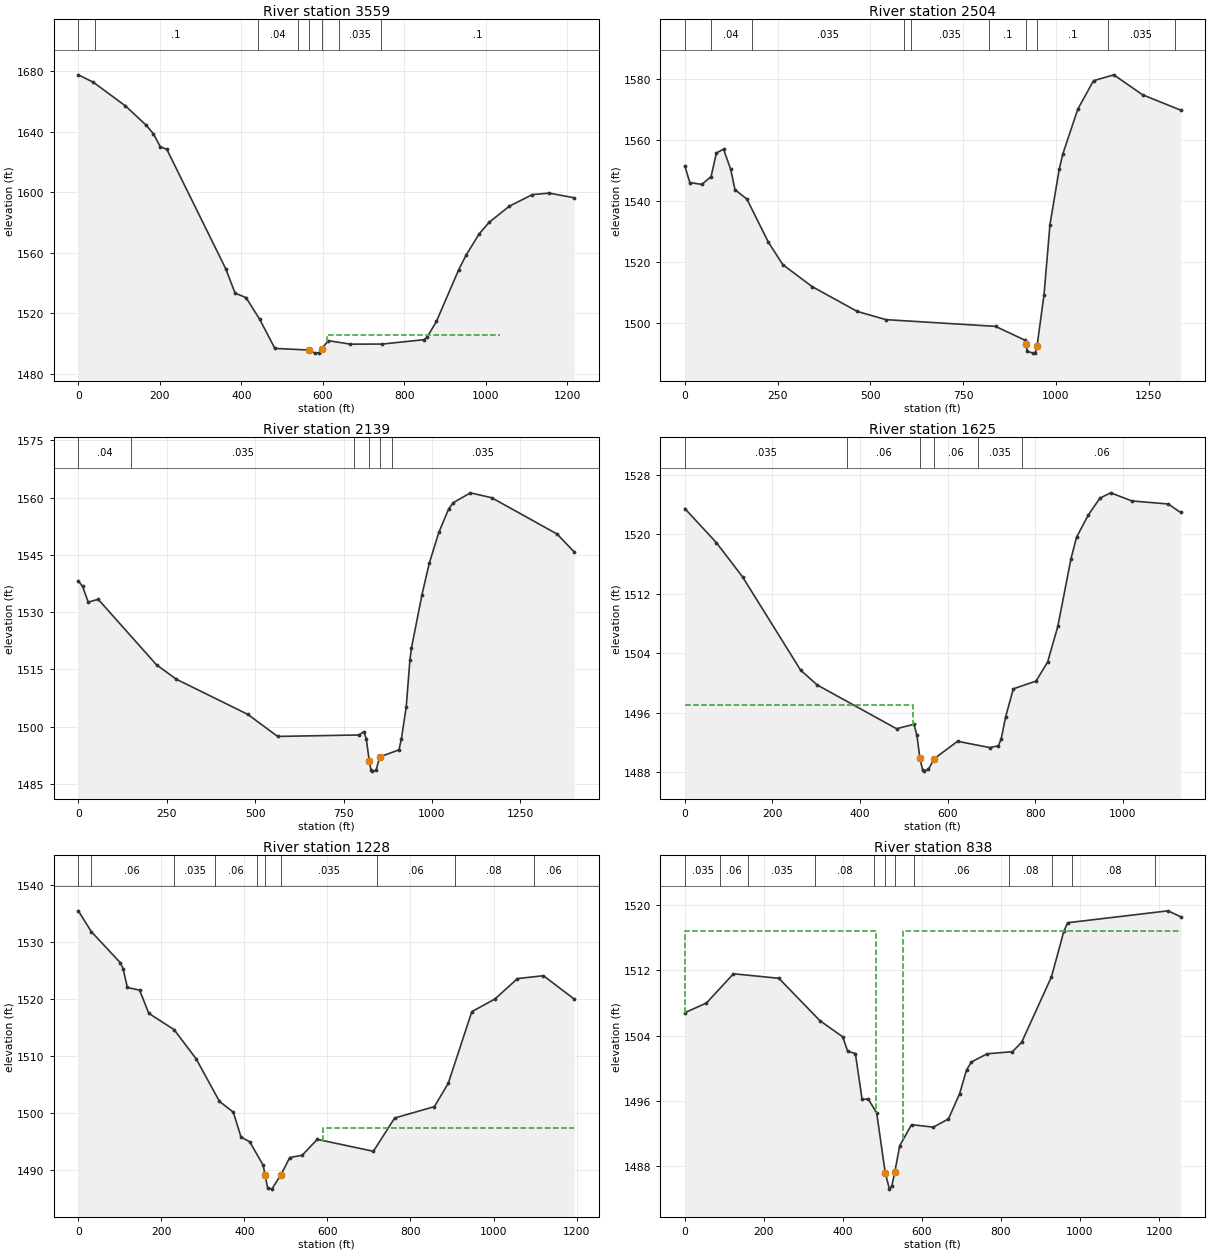
Type RM Length L Ch R = 1 ,3559    ,1030.9,1054.7,1037.5
XS GIS Cut Line= 4
     2048160.259      240477.8162047780.40441357240485.191097494
     2047505.745      240548.997     2046991.856      240759.066
#Sta/Elev= 30
       0 1677.75    36.8 1672.84   115.6 1657.21   167.1 1644.29   184.5 1638.68
   200.9 1630.31   217.3 1628.44   361.7 1549.57   384.8 1533.36   411.7 1530.42
   445.4 1515.97   482.4 1496.83   567.1 1495.71   580.1  1493.7   590.2 1493.85
     597 1496.54   613.8 1501.92     668 1499.64     746  1499.7   848.9  1502.6
   856.4 1504.38   879.1 1514.73   933.8 1548.93   951.5 1558.31   983.4 1572.38
  1008.2 1580.14  1057.9 1590.87  1114.6 1598.54  1155.8 1599.53  1217.1 1596.43
#Mann= 8 ,-1 , 0
       0    .035       0      40      .1       0  439.93     .04       0
  539.93      .1       0   567.1    .045       0     597      .1       0
  639.93    .035       0   741.9      .1       0
#XS Ineff= 1 ,-1
  610.93 1035.351505.926
Permanent Ineff=
       F
Bank Sta=567.1,597
XS Rating Curve= 0 ,0
Exp/Cntr=0.3,0.1

Type RM Length L Ch R = 1 ,2504    ,356,364.8,360.6
XS GIS Cut Line= 2
     2047984.912      239894.483     2046760.954      240429.205
#Sta/Elev= 30
       0 1551.61    13.5 1546.15    45.7 1545.51    70.8 1548.09    85.1 1555.82
   104.3 1557.08   123.7 1550.46   135.2  1543.8   167.4  1540.7   224.7 1526.66
   264.1  1519.2   342.9 1512.01   464.6 1503.86   541.6 1501.17     837 1498.96
   915.7 1494.46   918.6 1493.19   922.9 1490.75   938.9 1490.18   944.4 1490.36
     949 1492.55   967.8  1509.4   983.7 1532.34  1008.7  1550.5  1018.7 1555.66
  1058.9 1570.27    1101 1579.53  1155.6 1581.47    1233 1574.94  1335.7 1569.89
#Mann= 10 ,-1 , 0
       0     .06       0      70     .04       0     180    .035       0
     590      .1       0     610    .035       0     820      .1       0
   918.6    .045       0     949      .1       0    1140    .035       0
    1320      .1       0
Bank Sta=918.6,949
XS Rating Curve= 0 ,0
Exp/Cntr=0.3,0.1

Type RM Length L Ch R = 1 ,2139    ,506.8,514.6,513.8
XS GIS Cut Line= 3
2047869.07750929239657.043810276     2047081.622      239941.041
     2046538.656      240098.165
#Sta/Elev= 30
       0 1538.16    12.1 1536.76      28 1532.63    56.2 1533.36   221.3 1516.17
   277.1 1512.42   479.1 1503.21   563.7 1497.42   793.3  1497.8   807.3 1498.66
   814.2 1496.85  822.921490.973   827.7 1488.64   831.7 1488.32     842 1488.56
   852.3 1492.05   906.9  1493.9   913.8 1496.85   927.4 1505.19   937.7 1517.38
   942.1 1520.56   971.8 1534.53   992.3 1542.76  1019.6  1550.9  1047.3 1557.06
  1060.6 1558.71  1108.9 1561.28  1169.1 1559.99    1354 1550.48  1402.3 1545.79
#Mann= 6 ,-1 , 0
       0     .04       0     150    .035       0     780      .1       0
  822.92    .045       0   852.3      .1       0   887.1    .035       0
Bank Sta=822.92,852.3
XS Rating Curve= 0 ,0
Exp/Cntr=0.3,0.1

Type RM Length L Ch R = 1 ,1625    ,383.7,397.1,385.8
XS GIS Cut Line= 2
     2047597.759      239422.261     2046477.967      239588.927
#Sta/Elev= 30
       0 1523.44    72.2 1518.85   131.9 1514.25   264.6  1501.7   302.5 1499.72
   483.5 1493.84   523.3 1494.44   529.9 1492.99   536.8 1489.87   543.2 1488.23
   546.5 1488.14   556.3 1488.39   569.7 1489.82   622.8 1492.15   695.8 1491.31
   715.7 1491.53   722.3 1492.44   732.7 1495.48   750.1  1499.2     802 1500.25
   828.5 1502.82   851.7 1507.59   881.5 1516.62   894.4 1519.57   921.3 1522.57
   947.9 1524.84   972.4 1525.55  1020.8 1524.46  1103.8 1524.05  1132.1 1522.91
#Mann= 6 ,-1 , 0
       0    .035       0     370     .06       0   536.8    .045       0
   569.7     .06       0     670    .035       0     770     .06       0
#XS Ineff= 2 , 0
          520.25 1496.98
Permanent Ineff=
       F       F
Bank Sta=536.8,569.7
XS Rating Curve= 0 ,0
Exp/Cntr=0.3,0.1

Type RM Length L Ch R = 1 ,1228    ,411.6,389.3,359.9
XS GIS Cut Line= 3
     2047554.188       239125.97     2046835.438      239233.609
     2046467.382      239521.803
#Sta/Elev= 30
       0 1535.49    31.2 1531.85   101.1  1526.4   107.8 1525.36   118.1 1522.06
   147.6 1521.59   169.7 1517.53   230.5 1514.68   283.6 1509.58   339.9  1502.1
   373.2 1500.22   391.9 1495.86     413 1495.01   445.4 1490.89   449.5 1489.25
   456.1 1486.91     466 1486.73   488.3 1489.29   509.2 1492.26     539 1492.66
   575.5 1495.45   710.7 1493.36   761.8 1499.19   857.5 1501.18     891 1505.28
   947.7 1517.82  1003.5 1520.05  1057.7 1523.62  1120.2 1524.12  1194.2 1520.04
#Mann= 10 ,-1 , 0
       0    .035       0      30     .06       0     230    .035       0
     330     .06       0     430    .035       0   449.5    .045       0
   488.3    .035       0     720     .06       0  906.77     .08       0
 1096.77     .06       0
#XS Ineff= 2 , 0
                          588.68         1497.37
Permanent Ineff=
       F       F
Bank Sta=449.5,488.3
XS Rating Curve= 0 ,0
Exp/Cntr=0.5,0.3

Type RM Length L Ch R = 1 ,838     ,183.4,181.9,176.9
XS GIS Cut Line= 3
     2047075.021      238414.165     2046734.743      239181.526
     2046453.493      239487.081
#Sta/Elev= 30
       0 1506.81    54.9    1508   123.1 1511.58     238 1511.03     342 1505.83
   399.6 1503.85   412.1 1502.09   431.7  1501.8   448.6 1496.19   464.3 1496.21
   485.6 1494.52   507.1 1487.21   517.9 1485.18   523.9 1485.57   531.4 1487.28
   543.8 1490.49   573.7 1493.08   629.1 1492.78   667.2 1493.79   695.5 1496.88
   712.9 1499.79   725.3 1500.77   765.1 1501.77     829 1502.03   852.6  1503.2
   927.9 1511.21   959.2 1516.79   968.8 1517.84  1222.8  1519.3  1254.7 1518.58
#Mann= 12 ,-1 , 0
       0    .035       0      90     .06       0     160    .035       0
     330     .08       0     480     .04       0   507.1    .045       0
   531.4     .04       0     580     .06       0     820     .08       0
  929.42     .06       0  979.42     .08       0 1189.42     .06       0
#XS Ineff= 2 , 0
             485 1516.87     553         1516.87
Permanent Ineff=
       F       F
Bank Sta=507.1,531.4
XS Rating Curve= 0 ,0
Exp/Cntr=0.5,0.3

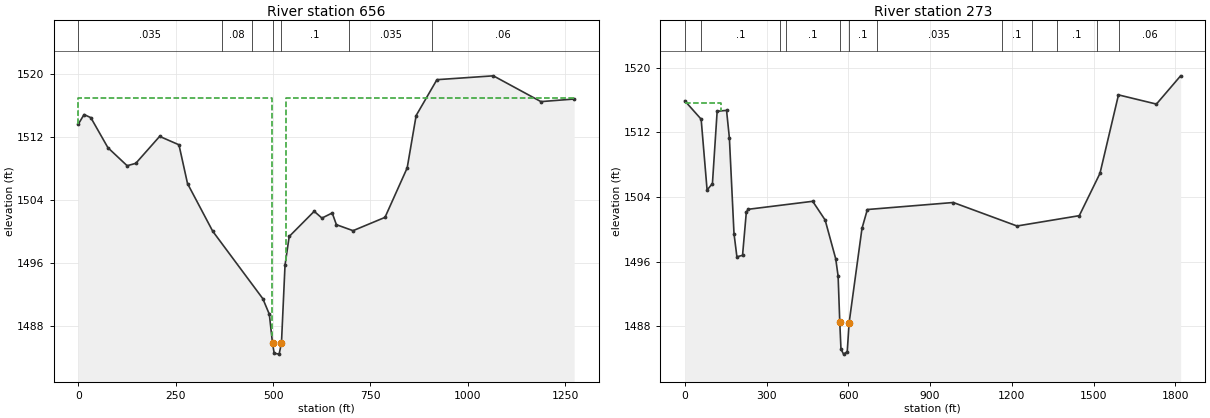
Type RM Length L Ch R = 1 ,656     ,381.1,383.4,380.2
XS GIS Cut Line= 4
2046866.07539854238295.9947368772046754.41473208238695.741763366
     2046581.098      239103.401     2046299.848      239408.956
#Sta/Elev= 30
       0 1513.65    14.7 1514.87    32.1 1514.47      76 1510.65   125.3 1508.36
   147.5 1508.66   208.8 1512.09   258.4 1511.02   280.4 1506.09   345.1 1500.03
   473.8 1491.45   490.5 1489.47 498.7091485.757     503 1484.51   515.6  1484.4
 521.641 1485.81   530.8 1495.72   541.5 1499.36   605.7 1502.56   625.6  1501.7
     652 1502.35   662.7 1500.86   705.5  1500.1   787.5 1501.79   844.5 1508.08
   867.5 1514.74   920.9  1519.3  1065.8 1519.79    1188 1516.51  1273.3 1516.84
#Mann= 7 ,-1 , 0
       0    .035       0     370     .08       0  445.05      .1       0
 498.709    .045       0 521.641      .1       0  695.05    .035       0
  908.02     .06       0
#XS Ineff= 2 , 0
          496.71 1516.96  532.34         1517.02
Permanent Ineff=
       F       F
Bank Sta=498.709,521.641
XS Rating Curve= 0 ,0
Exp/Cntr=0.5,0.3

Type RM Length L Ch R = 1 ,273     ,102.8,116.2,129.7
XS GIS Cut Line= 4
2046989.51896597238149.096731472 2046634.3681508238265.827760402
 2046125.8806174  239172.63052832046247.98884447239559.534520041
#Sta/Elev= 30
       0  1515.9      60 1513.63    81.8 1504.85   101.4 1505.66   118.7 1514.61
   153.2 1514.72   163.6  1511.3   180.5 1499.47   191.2 1496.58   211.9 1496.77
   225.8 1502.13   232.7 1502.47   469.3 1503.46   514.9 1501.14   553.7 1496.34
   562.5  1494.2  568.611488.489     573 1485.15   582.6 1484.53     596 1484.83
 602.7261488.368   650.1  1500.1   669.8 1502.44   985.1 1503.31  1218.9  1500.4
  1447.4 1501.68  1523.3 1506.92  1591.2 1516.64  1730.4  1515.5  1819.2    1519
#Mann= 12 ,-1 , 0
       0     .06       0      60      .1       0     350    .035       0
     370      .1       0  568.61    .045       0 602.726      .1       0
  703.84    .035       0 1163.84      .1       0 1273.84    .035       0
 1363.84      .1       0 1513.48    .035       0 1593.48     .06       0
#XS Ineff= 2 , 0
          131.81 1515.58
Permanent Ineff=
       F       F
Bank Sta=568.61,602.726
XS Rating Curve= 0 ,0
Exp/Cntr=0.3,0.1
Stream Node=KELLYCK         ,Main            , 0 , 0 ,Upstream end
Stream Node=KELLYCK         ,Main            , 0 , 1 ,Downstream end
Stream Node=River (Missing) ,Reach (Missing) , 0 , 0 ,Upstream end
Stream Node=River (Missing) ,Reach (Missing) , 0 , 1 ,Downstream end
LCMann Table=0

Chan Stop Cuts=-1
Use User Specified Reach Order=0
Composite Channel Slope=5